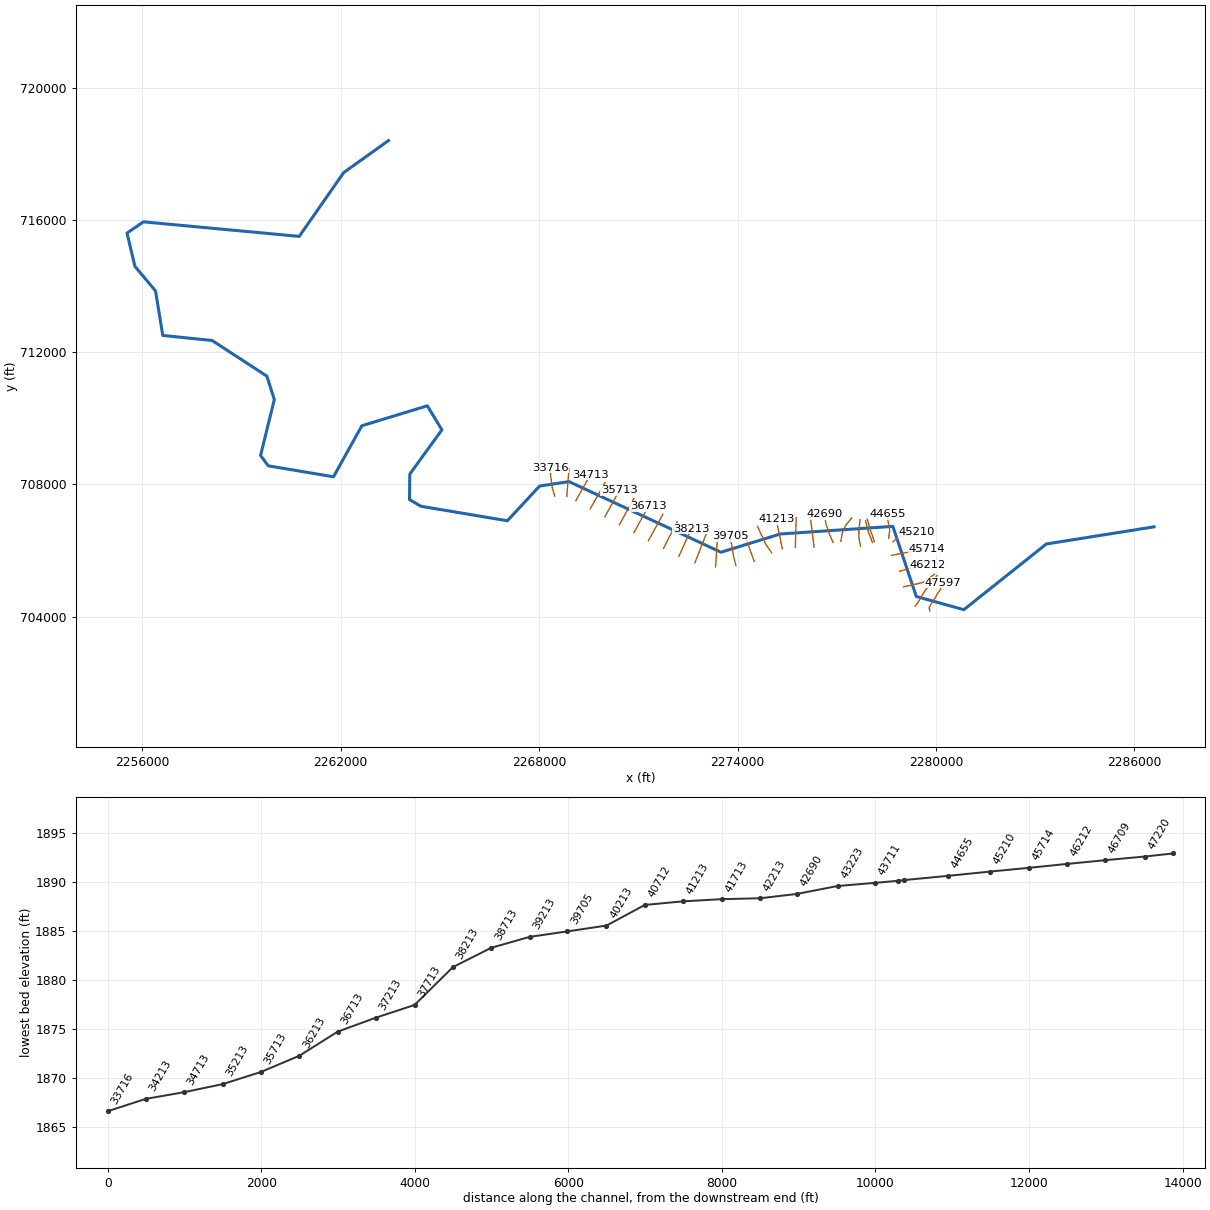
--- TYGVRV1.prj (project) ---

Proj Title=TYGVRV1
Current Plan=p01
Default Exp/Contr=0,0
English Units
Geom File=g01
Flow File=f01
Plan File=p01
BEGIN DESCRIPTION:
----------MODEL BY WOOD PLC 2022----------
AFH study
Randolph County, WV
HEC-RAS Version: RAS 6.2
Vertical Datum: NAVD88
Projection: NAD 1983 StatePlane West Virginia S FIPS 4702 (US Feet)
Terrain: 1-meter LIDAR (FEMA Region III 3DEP collected 2016-2018)
Land Use: 2019 NLCD
Hydrologic Method:
WV SIR2010-5033 regression equations
Additional Model Notes:
DS boundary condition starts outside of the county boundary, Barbour County/Upshur Zone A
END DESCRIPTION:
DSS Export Rating Curves= 0
DSS Export Rating Curve Sorted= 0
DSS Export Volume Flow Curves= 0
DXF OffsetX= 0
DXF OffsetY= 0
DXF ScaleX= 0
DXF ScaleY= 0

--- TYGVRV1.p01 (plan) ---

Plan Title=Floodplain
Program Version=4.00
Geom File=g01
Flow File=f01
K Sum by GR=0
Std Step Tol=0.01
Critical Tol=0.01
Num of Std Step Trials=20
Max Error Tol=0.3
Flow Tol Ratio=0.001
Split Flow NTrial=30
Split Flow Tol=0.02
Split Flow Ratio=0.02
Log Output Level=0
Friction Slope Method=1
Unsteady Friction Slope Method=2
Unsteady Bridges Friction Slope Method=1
Global Log Level=0
CheckData=False
Run HTab=0
Run UNet=0
Run PostProcess=0
UNET Theta=0
UNET Theta Warmup=0
UNET ZTol=0
UNET ZSATol=0
UNET MxIter=0
UNET MaxInSteps=0
UNET DtIC=0
UNET DtMin=0
UNET MaxCRTS=0
UNET WFStab=0
UNET SFStab=0
UNET WFX=0
UNET SFX=0
UNET DSS MLevel=0
UNET DZMax Abort=0
UNET Convert EG Bridges=0
UNET Use Existing IB Tables=0
UNET Froude Limit=0
UNET Froude Power=0
Write IC File=0
Echo Input=False
Echo Output=False
Write Detailed=0

--- TYGVRV1.f01 (steady flow) ---

Flow Title=Flow
Program Version=6.20
Number of Profiles= 1
Profile Names=P100yr
River Rch & RM=TYGVRV1,Main,47597
   23500
Boundary for River Rch & Prof#=TYGVRV1,Main            , 1
Up Type= 0
Dn Type= 3
Dn Slope=0.00279
DSS Import GetInterval= 0
DSS Import GetPeak= 0
DSS Import FillOption= 0

--- TYGVRV1.g01 (geometry) ---

Geom Title=Geometry
Program Version=6.20

River Reach=TYGVRV1         ,Main
Reach XY= 30
      2286592.23      706715.775     2283335.689      706197.232
     2280841.551      704209.592     2279404.558      704610.806
     2278695.985      706730.015     2275291.866      706498.943
     2273500.278      705948.174     2268908.308      708082.724
     2268016.621      707949.583     2267043.695      706899.733
     2264434.791      707336.691     2264085.177      707539.712
      2264093.22      708310.471     2265063.274      709648.592
     2264624.407      710375.667     2262644.555      709772.989
     2261786.134      708229.459     2259815.044      708560.721
     2259582.308      708873.756     2259998.146      710565.232
     2259772.546      711273.579     2258118.349      712351.122
     2256626.242      712503.651     2256407.719      713848.373
     2255785.061      714592.466     2255545.295      715600.758
     2256043.227      715939.128      2260751.06      715499.105
      2262095.84      717429.527     2263449.946      718396.261

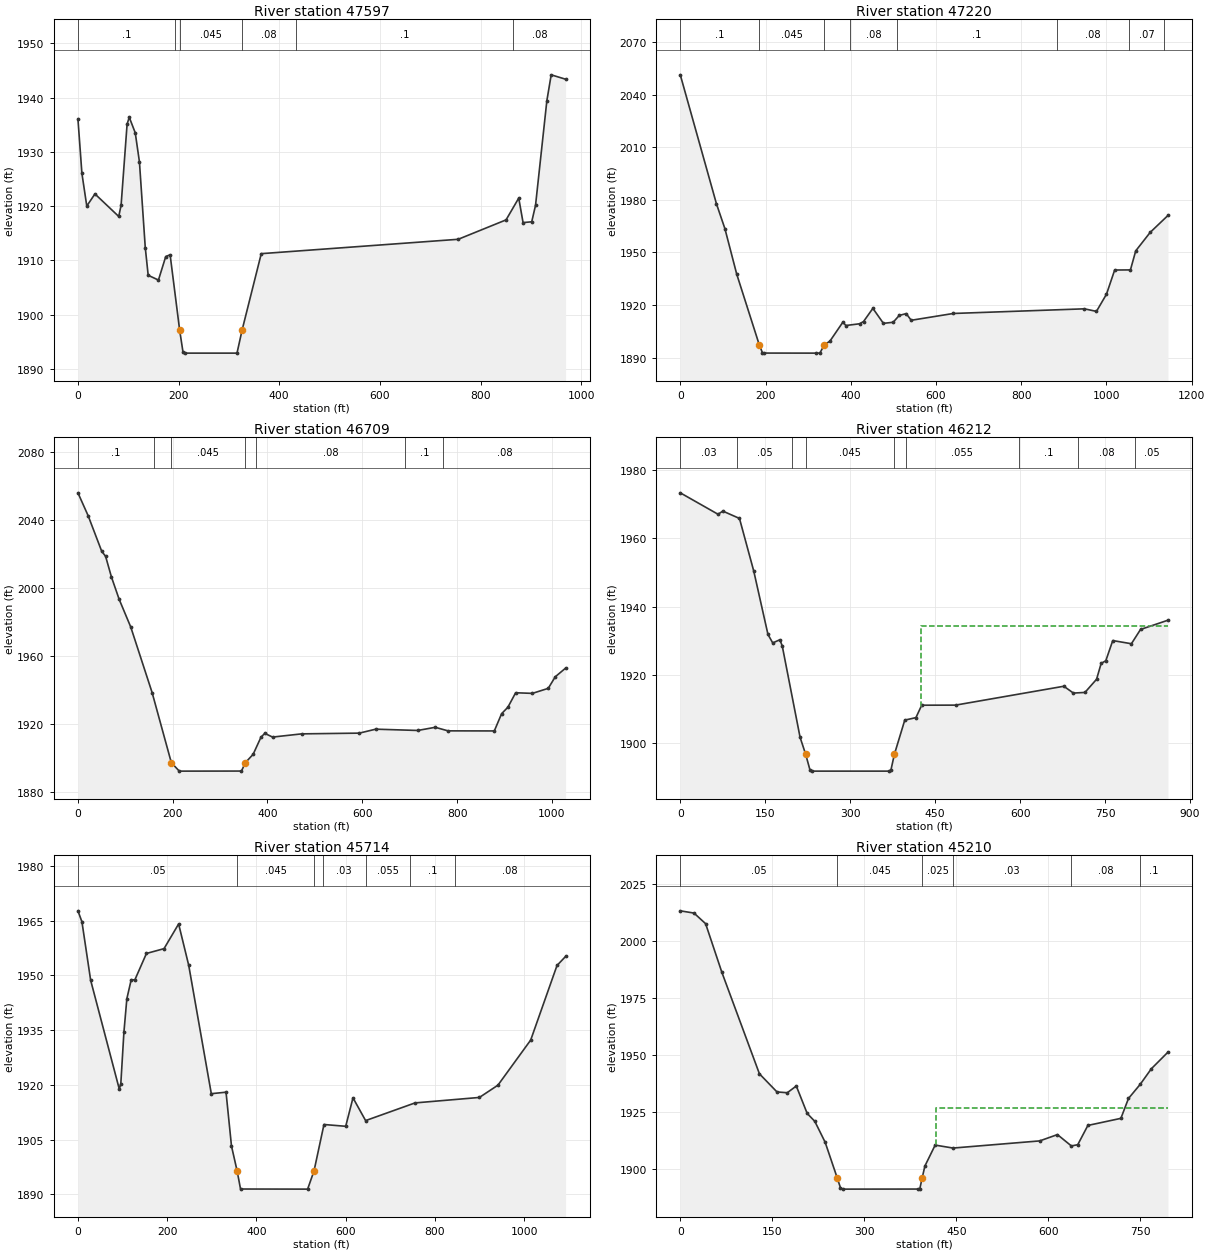
Type RM Length L Ch R = 1 ,47597   ,377.8,376.9,375.2
XS GIS Cut Line= 4
2279819.75863499704167.0612130152279789.11339395704276.713554307
2280128.51355817704820.6956746032280206.99906132705019.761236738
#Sta/Elev= 30
       0 1936.11     7.9 1926.05    17.6 1920.01    33.8 1922.25    81.1 1918.09
    85.8 1920.18    97.7 1935.12     102 1936.39   113.9 1933.52   122.2 1928.18
   133.8 1912.36   139.6 1907.24     160 1906.36   174.5  1910.7   183.2 1911.02
   202.1 1897.14   208.7 1893.12   213.4 1892.88   316.1 1892.88  326.24 1897.14
   364.3 1911.23   755.6 1913.88   850.7 1917.46   875.9 1921.48   884.5 1916.96
   901.7 1917.11   909.3 1920.16   931.8 1939.46   940.4 1944.22     969 1943.41
#Mann= 6 ,-1,0
       0      .1       0  193.85    .025       0   202.1    .045       0
  326.24     .08       0  433.85      .1       0  865.03     .08       0
Bank Sta=202.1,326.24
XS Rating Curve= 0 ,0
Exp/Cntr=0.3,0.1

Type RM Length L Ch R = 1 ,47220   ,571.3,510.4,446.2
XS GIS Cut Line= 4
2279367.12093762704312.9006641322279467.32060464704448.656076095
2279674.62059148704796.8131034632280031.46845645705241.587826552
#Sta/Elev= 30
       0 2051.37    84.9 1977.75   104.7 1963.59   132.5 1937.57  185.181897.417
   192.6 1892.89   197.3 1892.59     319 1892.56   327.6  1892.6  338.161897.416
   350.9 1899.33   381.5 1910.24   388.6 1908.32   420.7 1909.31     430  1910.6
   451.9  1918.1   476.6 1909.55   499.5 1910.17   513.8 1914.08   530.1 1915.11
   541.8  1911.3   640.7 1915.19     948 1917.84   976.5 1916.39    1000 1926.19
  1019.2 1939.98  1056.2 1940.05  1068.6 1950.91  1102.6 1961.48  1144.2 1971.11
#Mann= 8 ,-1,0
       0      .1       0  185.18    .045       0  338.16    .025       0
  398.73     .08       0  508.73      .1       0  883.93     .08       0
 1053.93     .07       0 1133.93      .1       0
Bank Sta=185.18,338.16
XS Rating Curve= 0 ,0
Exp/Cntr=0.3,0.1

Type RM Length L Ch R = 1 ,46709   ,499.6,497.6,495.4
XS GIS Cut Line= 4
2279019.06430772704902.3532906052279181.13299772 704936.60168617
2279605.83519247705032.2152692822279953.96274173705281.300456829
#Sta/Elev= 30
       0  2055.9    21.6 2042.41    50.2 2021.51    58.4 2018.55    70.6  2006.5
      87 1993.26   111.5 1976.93   156.5 1938.44   197.11897.173   213.9 1892.19
   345.1 1892.23  353.321897.179   369.7 1902.08   386.2 1912.12   394.3  1914.4
   410.7 1912.22   472.2 1914.11   593.7 1914.54   628.4 1916.87     717 1916.11
   753.9 1917.97   780.9 1915.88   878.6 1915.83     894 1925.98   907.3  1929.8
   923.6 1938.29   958.9 1937.93   992.4 1940.88  1007.2 1947.69    1029 1952.78
#Mann= 7 ,-1,0
       0      .1       0     160    .025       0   197.1    .045       0
  353.32    .025       0  375.65     .08       0  690.98      .1       0
  770.98     .08       0
Bank Sta=197.1,353.32
XS Rating Curve= 0 ,0
Exp/Cntr=0.3,0.1

Type RM Length L Ch R = 1 ,46212   ,499.7,498.1,496.5
XS GIS Cut Line= 4
2278896.56616242705369.1677162422279075.88003604705425.922051672
2279522.17947014705513.6742940292279735.54258463705558.119145302
#Sta/Elev= 30
       0 1973.32    66.7 1967.04    75.1 1967.97   104.5 1965.82   129.7 1950.41
   154.8 1931.84   163.2 1929.36   175.8 1930.29     180 1928.49   211.5 1901.71
  221.351896.729   229.1 1892.08   233.2 1891.81   367.8 1891.81   371.8 1892.08
  377.981896.729   396.3 1906.75     416 1907.48   426.2 1911.12     486 1911.14
   677.1 1916.67     694 1914.67   714.4 1914.86   734.9 1918.72     743 1923.36
   751.2 1924.14   763.5 1930.05   796.4 1929.12   812.5  1933.3   860.9 1936.01
#Mann= 9 ,-1,0
       0     .03       0     100     .05       0  198.08      .1       0
  221.35    .045       0  377.98    .025       0  398.08    .055       0
  598.08      .1       0  702.93     .08       0  802.93     .05       0
#XS Ineff= 2 , 0
                          424.46         1934.45
Permanent Ineff=
       F       F
Bank Sta=221.35,377.98
XS Rating Curve= 0 ,0
Exp/Cntr=0.3,0.1

Type RM Length L Ch R = 1 ,45714   ,495.5,504,512.5
XS GIS Cut Line= 4
2278651.35333131 705848.243192132278963.28194998705913.583883073
2279264.35525854  705967.16863932279727.16801813706036.822500824
#Sta/Elev= 30
       0 1967.72       9 1964.71    28.5 1948.69    92.7 1918.82    96.1 1920.32
     103 1934.38   109.6 1943.62   119.4 1948.83   127.5 1948.78   153.5 1956.03
   192.9 1957.35   225.6 1964.12   248.2 1952.78   298.8 1917.58   331.8 1917.99
     344 1903.24  356.561896.443   364.3 1891.44   514.6 1891.41  528.991896.442
   551.2 1909.13   599.9 1908.64   616.2 1916.44   644.5  1910.2   755.2 1915.05
   899.4 1916.55   940.9 1919.91  1014.3 1932.28  1073.3 1952.74  1092.5 1955.21
#Mann= 7 ,-1,0
       0     .05       0  356.56    .045       0  528.99    .025       0
   548.7     .03       0   644.5    .055       0   744.5      .1       0
   844.5     .08       0
Bank Sta=356.56,528.99
XS Rating Curve= 0 ,0
Exp/Cntr=0.3,0.1

Type RM Length L Ch R = 1 ,45210   ,440.6,554.6,652.3
XS GIS Cut Line= 4
2278700.84673032 706262.55744732 2278848.1158028706389.239465201
2279148.35244922706478.109720807 2279426.3361453706551.106143401
#Sta/Elev= 30
       0  2013.2    22.4 2012.21    41.3 2007.55    67.7 1986.27     129 1941.65
   157.6  1933.7   174.4 1933.34   189.1  1936.3   206.8 1924.28   219.3 1920.77
   236.1 1911.62  255.911895.857   261.1  1891.6   265.2 1891.03   387.4 1891.06
   390.4 1891.18  394.161895.863   398.7 1901.18   415.4 1910.36   444.6 1909.06
   585.8  1912.2   614.7 1914.97   637.4 1909.99   647.8 1910.53   664.3 1918.99
   718.1  1922.1   730.5 1930.84   749.6 1937.03   767.7 1943.86   794.8 1951.16
#Mann= 6 ,-1,0
       0     .05       0  255.91    .045       0  394.16    .025       0
   444.6     .03       0   637.4     .08       0   749.6      .1       0
#XS Ineff= 2 , 0
                           416.4         1926.49
Permanent Ineff=
       F       F
Bank Sta=255.91,394.16
XS Rating Curve= 0 ,0
Exp/Cntr=0.3,0.1

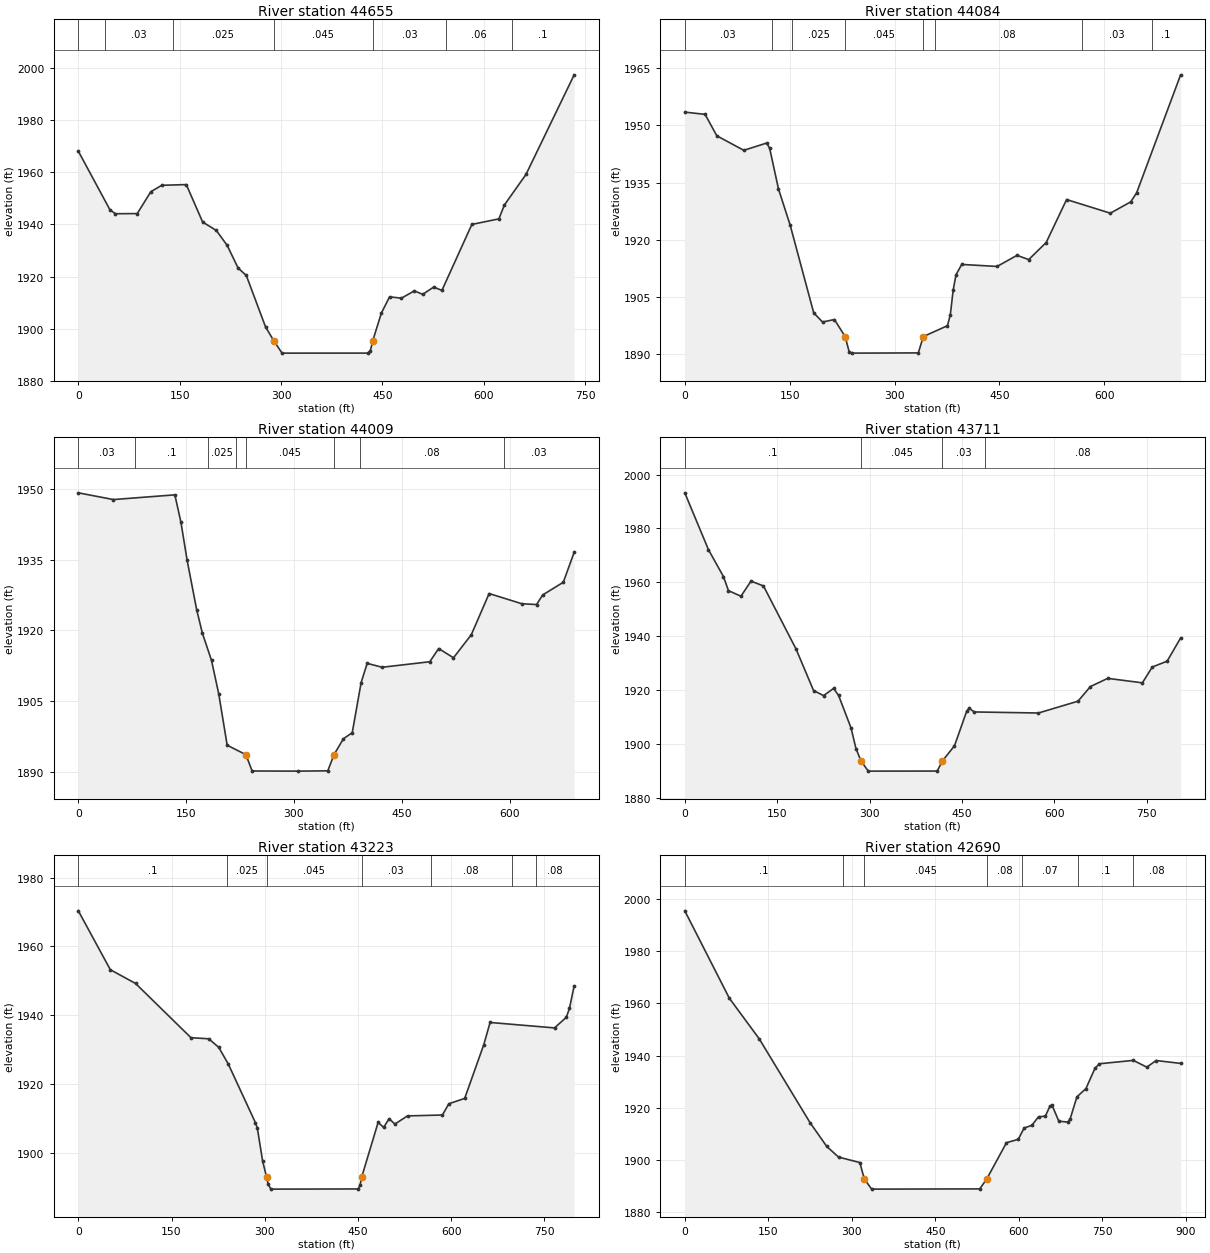
Type RM Length L Ch R = 1 ,44655   ,558.1,570.8,582.4
XS GIS Cut Line= 4
2278568.96700994706370.7861821852278602.71165778706623.316500774
2278544.55794137706914.3561984152278537.33634713707096.419714142
#Sta/Elev= 30
       0 1968.15    46.8 1945.63    54.9 1944.13    87.2 1944.19   107.3 1952.59
   123.5 1955.05   159.8 1955.32     184 1940.93   204.2 1937.71   220.3 1931.96
   236.5 1923.26   248.6 1920.42   277.1 1900.64  289.49 1895.24   301.5 1890.59
     428  1890.6   432.1 1891.43  435.621895.239   448.4 1905.92   460.6  1912.2
   478.2  1911.7   497.3 1914.51   509.6 1913.16   525.9 1915.96   538.1 1914.68
   582.4 1940.02   622.4 1942.16   630.5 1947.47   662.5 1959.22   733.8 1997.48
#Mann= 7 ,-1,0
       0      .1       0      40     .03       0     140    .025       0
  289.49    .045       0  435.62     .03       0  544.77     .06       0
  641.57      .1       0
Bank Sta=289.49,435.62
XS Rating Curve= 0 ,0
Exp/Cntr=0.3,0.1

Type RM Length L Ch R = 1 ,44084   ,74.9,75.4,72.8
XS GIS Cut Line= 6
2278135.25388699706269.5736968682278072.45590412706465.193406704
2278021.55722105706598.1770586522278016.13004047706619.110469473
2278010.41498113 706646.600298452277922.23341273706945.512108462
#Sta/Elev= 30
       0  1953.5      29 1952.91    45.8 1947.28    84.4 1943.46   117.2 1945.38
   121.4 1943.97     134 1933.31   150.8 1923.74   184.4 1900.74     197 1898.34
     214 1898.99  229.34 1894.51   235.2 1890.46   239.6 1890.16     334 1890.22
341.16061894.505   375.7 1897.37   379.8 1900.25   383.9 1906.76   387.9 1910.74
   396.1 1913.47   446.7 1912.94   475.2 1915.86   491.9 1914.74   516.9 1919.23
   546.1 1930.52   608.7 1926.94   637.9 1929.92   646.3 1932.31   709.2  1963.3
#Mann= 8 ,-1,0
       0     .03       0   124.4      .1       0  153.09    .025       0
  229.34    .045       0341.1606    .025       0  357.86     .08       0
   567.6     .03       0   667.6      .1       0
Bank Sta=229.34,341.1606
XS Rating Curve= 0 ,0
Exp/Cntr=0.3,0.1

Type RM Length L Ch R = 1 ,44009   ,328.3,297.9,282.8
XS GIS Cut Line= 6
 2278078.8943346706243.9853232662278052.82502544706307.861072106
2278011.81765297706421.0640051452277988.24145796706475.803389442
2277958.77962051706553.3345406332277869.14010979706899.789199752
#Sta/Elev= 30
       0 1949.22    48.8 1947.79   134.3 1948.79   142.8 1942.95   151.3 1934.96
   164.6 1924.43   172.5 1919.45   185.3 1913.61   195.3 1906.56   207.1  1895.6
   233.2 1893.58   241.8 1890.12   305.5 1890.09   347.1 1890.15   355.8  1893.6
   368.8 1896.97   381.1 1898.24   393.5 1908.91   401.9 1912.99   422.7 1912.16
     489 1913.33   501.4 1916.14     522 1914.17   546.8 1919.08   571.6 1927.82
     617 1925.66   637.6 1925.48   646.1 1927.52   674.8 1930.22   689.9 1936.59
#Mann= 8 ,-1,0
       0     .03       0   78.99      .1       0  180.17    .025       0
  219.38     .08       0   233.2    .045       0   355.8    .025       0
  391.65     .08       0  591.68     .03       0
Bank Sta=233.2,355.8
XS Rating Curve= 0 ,0
Exp/Cntr=0.3,0.1

Type RM Length L Ch R = 1 ,43711   ,522.3,488.5,465.4
XS GIS Cut Line= 4
2277716.38118372706131.4483088632277669.39122029706388.615423618
     2277673.287706604.0943701042277703.95400342706931.008640167
#Sta/Elev= 30
       0  1993.2    38.4 1972.11    62.8  1962.1    70.9 1956.89    91.2 1954.81
   107.5 1960.43   127.8 1958.62   180.7  1935.2   209.1 1919.81   225.4 1917.92
   241.7 1920.59   249.8 1917.97     270  1905.9     278 1898.27  286.131893.678
     298 1889.88     410 1889.91  418.411893.679     438 1899.28     458 1912.23
     462 1913.23     470 1911.85   574.4 1911.46   638.7 1915.85   658.8 1921.28
   686.9 1924.32   743.2 1922.66   759.3 1928.54   783.4  1930.7   805.3 1939.32
#Mann= 4 ,-1,0
       0      .1       0  286.13    .045       0  418.41     .03       0
  486.94     .08       0
Bank Sta=286.13,418.41
XS Rating Curve= 0 ,0
Exp/Cntr=0.3,0.1

Type RM Length L Ch R = 1 ,43223   ,450.9,532.6,592.2
XS GIS Cut Line= 4
2277124.18977079706278.4294200082277170.65206682706550.092673761
 2277269.6207546706759.5129480412277450.63053461706987.090952301
#Sta/Elev= 30
       0 1970.33    51.5 1953.24    92.1 1949.25   181.3 1933.51   209.8 1933.19
     226 1930.71   241.5 1925.81   285.1 1908.81   288.1 1907.26   296.7 1897.61
  303.091892.998   305.6 1890.92     310 1889.56   450.3 1889.61   453.3 1890.64
  455.951892.992   482.5 1908.93   491.4 1907.48   500.2 1910.01   509.4 1908.45
   529.8 1910.81     586 1911.07   596.3 1914.33   621.8 1915.89   652.6 1931.51
   662.7 1937.93   766.4 1936.35   785.4 1939.44   790.5 1942.08     798 1948.55
#Mann= 7 ,-1,0
       0      .1       0     240    .025       0  303.09    .045       0
  455.95     .03       0  567.24     .08       0  697.24      .1       0
  737.24     .08       0
Bank Sta=303.09,455.95
XS Rating Curve= 0 ,0
Exp/Cntr=0.3,0.1

Type RM Length L Ch R = 1 ,42690   ,504,477,459.1
XS GIS Cut Line= 4
2276886.08587016706246.1859513092276790.50735102706471.703251131
2276672.87255886706801.8490154672276625.38442145707092.955364777
#Sta/Elev= 30
       0 1995.54      80    1962   133.6 1946.45   224.8  1914.3     255 1905.11
   276.1 1901.04   314.4 1898.95  322.221892.672   335.6 1888.75   529.7 1888.84
  542.291892.676   577.7 1906.57   598.8 1907.86   609.4 1912.21   623.1 1913.21
   635.3 1916.54   647.4 1916.71   655.5  1920.5   659.6  1920.9   671.7 1914.82
   687.9 1914.48     692 1915.69   704.2 1924.17   720.4 1927.35   736.6 1935.12
   744.7 1936.86   805.5 1938.15   829.8 1935.55   846.3  1938.1   890.4 1936.99
#Mann= 7 ,-1,0
       0      .1       0  284.94    .025       0  322.22    .045       0
  542.29     .08       0  605.41     .07       0  705.41      .1       0
  805.41     .08       0
Bank Sta=322.22,542.29
XS Rating Curve= 0 ,0
Exp/Cntr=0.3,0.1

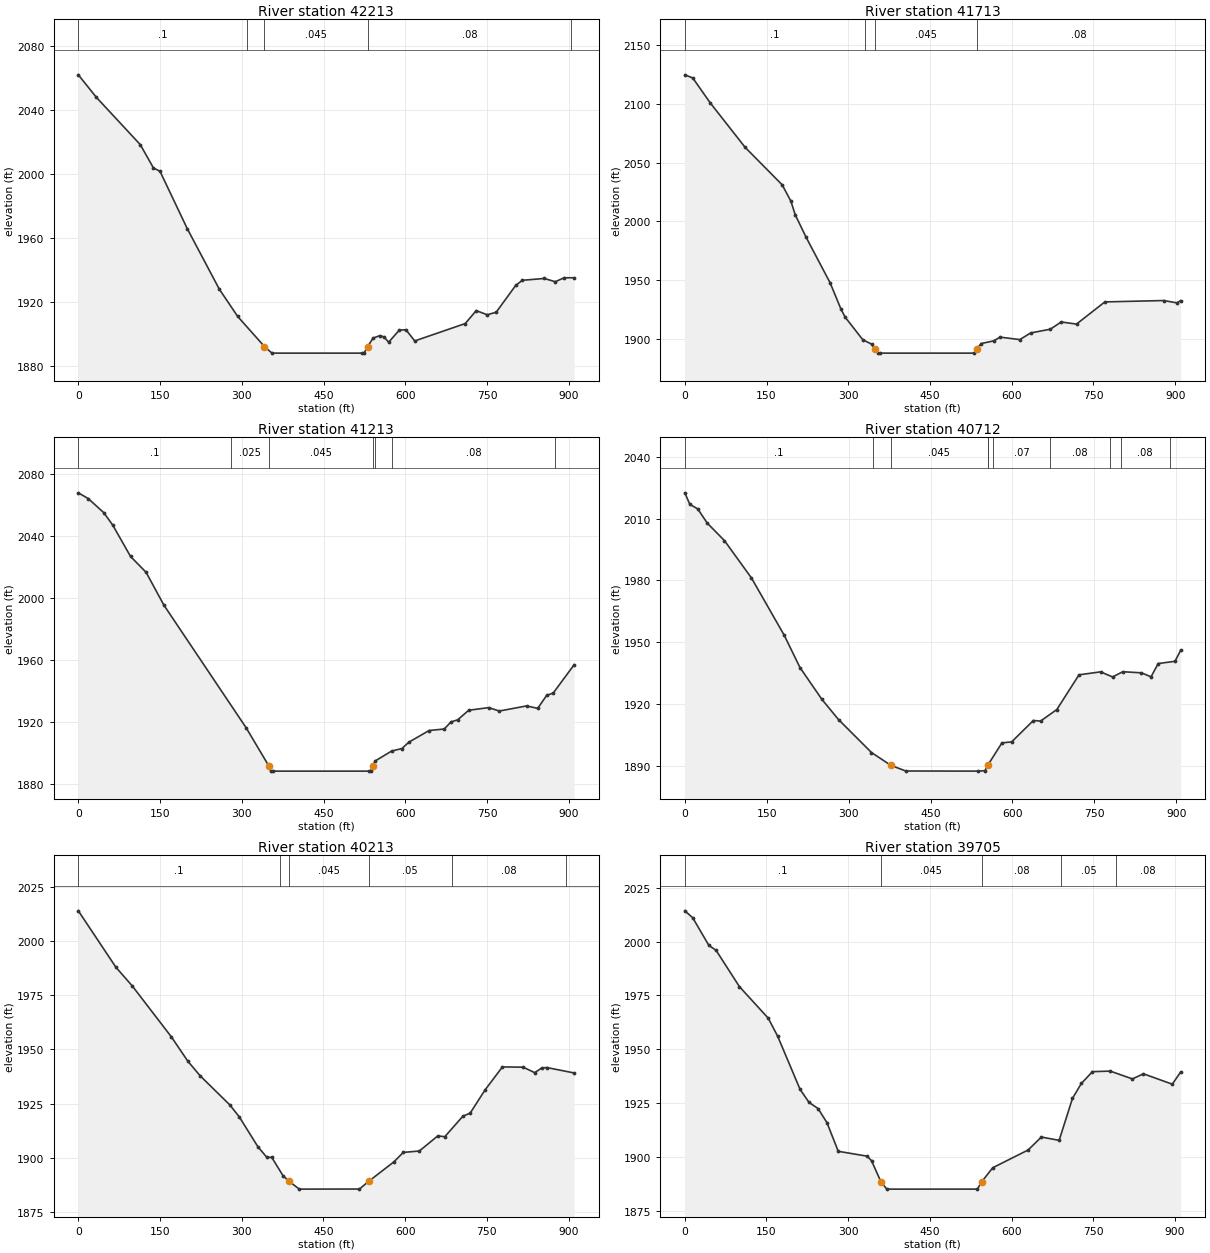
Type RM Length L Ch R = 1 ,42213   ,516.1,500,487.6
XS GIS Cut Line= 3
     2276314.434      706104.418       2276258.7      706555.991
     2276202.966      707007.565
#Sta/Elev= 30
       0 2062.01      33    2048   113.6 2018.49   137.8 2003.94   149.9 2001.79
     200 1965.94   258.7 1928.26   292.5 1911.18  341.661892.402   355.4 1888.31
   520.7 1888.31   524.7 1888.55  530.981892.402   540.8 1897.66   552.9 1899.18
     561 1898.46   569.5 1895.13   589.2  1902.7   601.3  1902.9   617.4 1895.92
   710.1 1906.77   730.3 1914.85   750.4 1912.26   766.9 1913.83   802.7 1930.57
   814.9 1933.77   855.2 1934.91   875.4 1932.87   891.5 1935.34     910 1935.36
#Mann= 5 ,-1,0
       0      .1       0     310    .025       0  341.66    .045       0
  530.98     .08       0     905     .07       0
Bank Sta=341.66,530.98
XS Rating Curve= 0 ,0
Exp/Cntr=0.3,0.1

Type RM Length L Ch R = 1 ,41713   ,475.7,500,519.4
XS GIS Cut Line= 3
     2275749.041      706086.562     2275759.776      706541.465
     2275775.262      706996.196
#Sta/Elev= 30
       0 2124.54    14.6  2121.9    46.6 2100.78   110.6 2063.03   178.7 2031.14
   194.7 2017.28   202.7 2005.67   222.7 1986.56   266.7 1947.93   286.7 1925.54
   294.5 1918.64   326.7 1899.58   342.7  1895.9  348.321892.086   354.7 1888.26
   358.7 1888.22   530.8 1888.22  536.231892.078   544.2 1896.39   566.8 1898.61
   578.8 1901.79   614.8  1899.7   634.8 1905.35   670.9 1908.55   690.9 1914.69
   718.9 1912.86   770.9 1931.71     879 1932.88     903 1930.91     910 1932.75
#Mann= 4 ,-1,0
       0      .1       0     330    .025       0  348.32    .045       0
  536.23     .08       0
Bank Sta=348.32,536.23
XS Rating Curve= 0 ,0
Exp/Cntr=0.3,0.1

Type RM Length L Ch R = 1 ,41213   ,478.5,501.2,522.3
XS GIS Cut Line= 3
     2275354.574      706047.321     2275262.976      706493.005
     2275171.378       706938.69
#Sta/Elev= 30
       0 2067.76    18.2 2064.04    46.8 2054.92    63.2 2046.88    95.8 2026.67
   124.4 2016.41   157.1 1995.18   308.2 1915.88  349.34 1891.51   353.1 1888.06
   357.2    1888   532.8    1888   536.8  1888.1  540.531891.518     545  1894.6
     575 1900.97     594 1902.61   606.6  1906.7   643.8 1914.24   671.6 1915.21
   683.9 1919.78   696.1 1921.11   716.5 1927.32   753.3 1929.03   772.5 1926.82
   822.7 1930.12   843.1 1928.55   859.5  1936.9   871.7 1938.48     910 1956.75
#Mann= 7 ,-1,0
       0      .1       0     280    .025       0  349.34    .045       0
  540.53     .08       0     545     .05       0     575     .08       0
     875     .03       0
Bank Sta=349.34,540.53
XS Rating Curve= 0 ,0
Exp/Cntr=0.3,0.1

Type RM Length L Ch R = 1 ,40712   ,504.7,498.8,490.9
XS GIS Cut Line= 4
     2275031.981      705932.0832274855.32904031706192.926893516
2274713.08153441706493.9733832562274605.16246688706730.512212218
#Sta/Elev= 30
       0 2022.44     9.3 2016.84    23.7 2014.66      41  2007.8    72.7 1999.27
   122.1 1981.19   182.1 1953.44   210.9 1937.82   251.2 1922.35   281.5 1912.61
   341.9 1896.64  377.561890.397   404.7  1887.7   536.5 1887.63   549.8 1887.83
  554.611890.395   580.8 1901.32   598.5 1901.79   638.3 1912.15   651.5 1911.88
   681.3 1917.46   721.9 1934.28   761.4 1935.72   783.4 1933.26   802.1 1935.78
   836.2 1935.25   853.8 1933.32     867 1939.75   897.7 1940.83     908 1946.11
#Mann= 10 ,-1,0
       0      .1       0  345.03    .025       0  377.56    .045       0
  554.61    .025       0  555.03     .05       0  565.03     .07       0
  667.99     .08       0  777.99     .07       0  797.99     .08       0
  887.99     .05       0
Bank Sta=377.56,554.61
XS Rating Curve= 0 ,0
Exp/Cntr=0.3,0.1

Type RM Length L Ch R = 1 ,40213   ,524,508.2,493.5
XS GIS Cut Line= 3
      2274506.36      705672.348      2274349.81      706099.551
     2274200.861      706529.573
#Sta/Elev= 30
       0 2013.87      69 1987.84    98.9 1979.27   170.7 1955.77   201.1  1944.5
   223.7 1937.77   277.8 1924.44   295.4 1918.86   329.7 1905.04     346 1900.21
   355.1 1900.16   375.8 1891.68  386.33 1889.24   405.6 1885.53     516 1885.58
  533.541889.241   579.5 1898.16   596.4 1902.45     626 1903.12   659.9  1910.1
   672.6 1909.69   705.9 1919.17   719.2 1920.57   746.4 1931.22   778.4 1941.89
   816.5 1941.77   837.7 1939.24   850.6 1941.41     860  1941.6   910.1  1939.1
#Mann= 6 ,-1,0
       0      .1       0     370    .025       0  386.33    .045       0
  533.54     .05       0  684.98     .08       0  894.98     .05       0
Bank Sta=386.33,533.54
XS Rating Curve= 0 ,0
Exp/Cntr=0.3,0.1

Type RM Length L Ch R = 1 ,39705   ,513.3,491.8,473.4
XS GIS Cut Line= 4
     2273952.219      705539.6912273878.69446727705836.006907399
2273829.41625621706148.594570209     2273774.395      706432.147
#Sta/Elev= 30
       0 2014.26    14.5 2011.06    44.2  1998.2    57.4 1995.92   100.4 1979.01
   153.2 1964.38   170.5 1956.03   211.7 1931.29   228.2 1925.22   244.7  1922.4
   261.2 1915.77   281.8 1902.52   334.8 1900.26   342.9 1898.17  360.221888.338
     371 1884.94   537.3 1884.95   545.21888.336   565.6 1894.89   630.5 1903.12
   654.9 1909.15   687.5  1907.6     712 1927.11   728.3 1934.05   748.7 1939.53
   781.3 1939.78     822 1936.16   842.4 1938.52   895.3  1933.7   910.6 1939.37
#Mann= 5 ,-1,0
       0      .1       0  360.22    .045       0   545.2     .08       0
  691.75     .05       0  791.75     .08       0
Bank Sta=360.22,545.2
XS Rating Curve= 0 ,0
Exp/Cntr=0.3,0.1

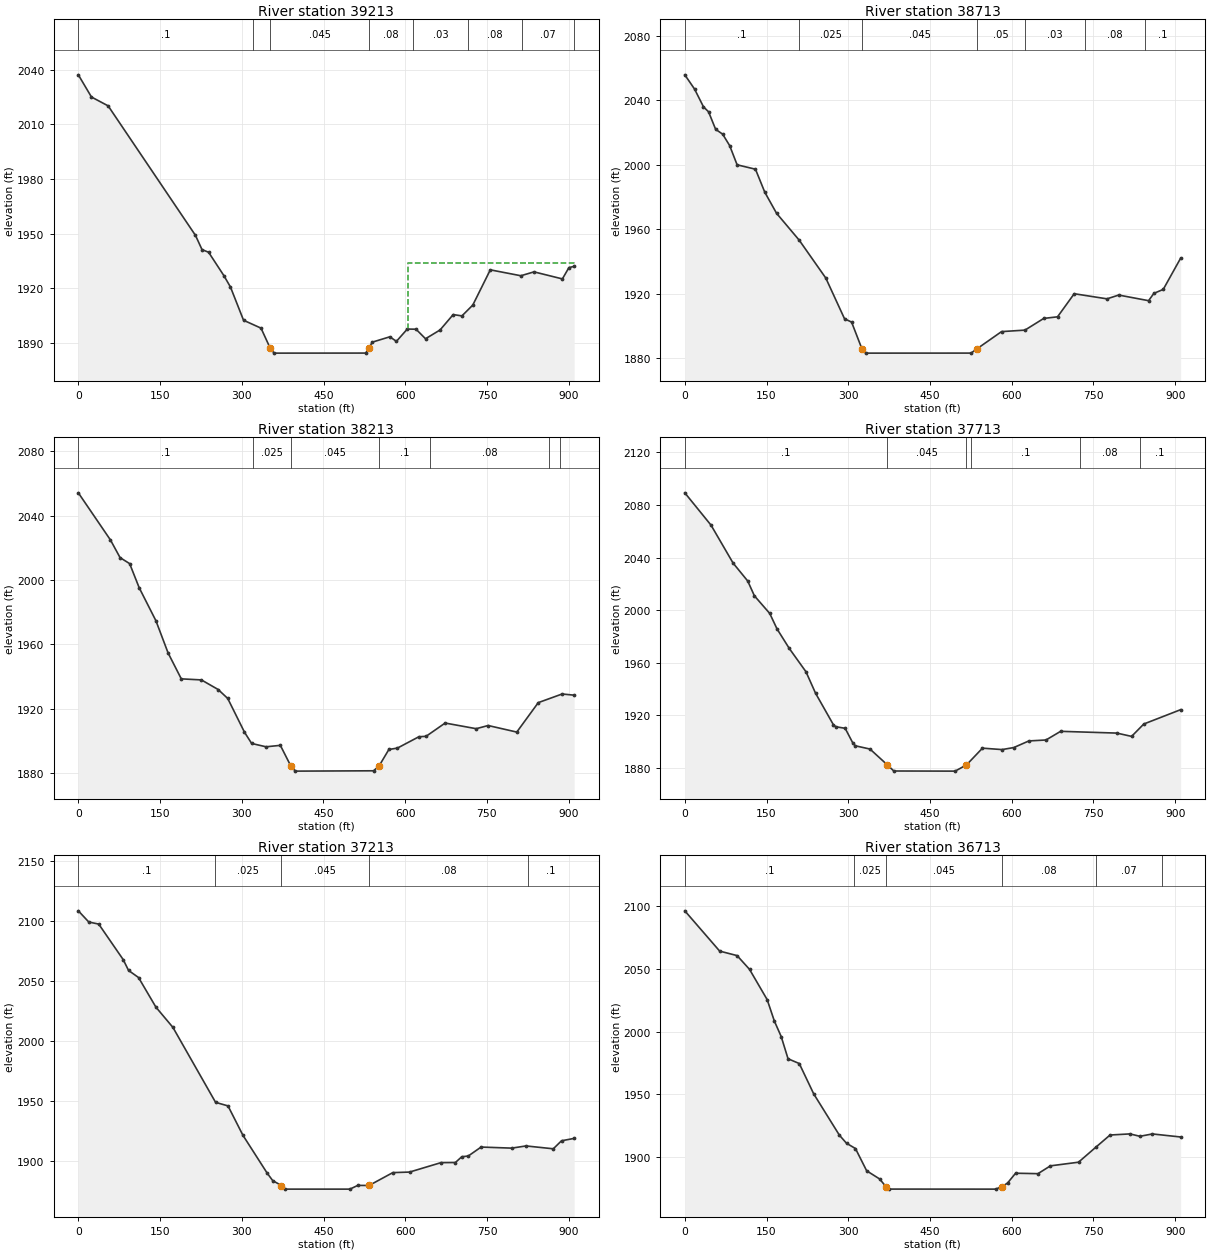
Type RM Length L Ch R = 1 ,39213   ,536.8,500,474.4
XS GIS Cut Line= 3
     2273337.221      705502.583     2273365.958      705956.675
     2273394.696      706410.766
#Sta/Elev= 30
       0 2037.12    24.1 2024.94    54.7 2020.09     215    1949     227  1941.2
   239.1 1939.74   267.1 1926.93   279.2 1920.67   303.2 1902.43   335.3 1898.09
  352.191887.072   359.3 1884.38   527.6 1884.41  532.841887.073   539.7 1890.42
   571.7 1893.34   583.8 1890.85   603.8  1897.6   619.8  1897.5   637.2 1892.27
   663.9 1897.09     688 1905.54     704 1904.81     724 1910.77   756.1 1930.09
   812.2 1926.85   836.3 1928.98   888.4 1925.11   900.4 1931.33     910    1932
#Mann= 8 ,-1,0
       0      .1       0     320    .025       0  352.19    .045       0
  532.84     .08       0     615     .03       0     715     .08       0
     815     .07       0     910      .1       0
#XS Ineff= 2 , 0
                          605.78         1933.96
Permanent Ineff=
       F       F
Bank Sta=352.19,532.84
XS Rating Curve= 0 ,0
Exp/Cntr=0.3,0.1

Type RM Length L Ch R = 1 ,38713   ,508.1,500,496
XS GIS Cut Line= 3
     2272712.305      705632.532     2272879.537      706055.685
     2273046.769      706478.838
#Sta/Elev= 30
       0 2055.73    17.9 2046.91    34.3 2035.89    43.6 2032.82    56.6 2021.96
    69.5 2018.96    82.4 2011.83      96 1999.97   129.7 1997.24   146.9 1982.92
   168.4 1969.93     210 1953.26   258.8 1929.78   293.2 1904.53   306.1 1902.51
  324.941886.064   331.9 1883.27   525.4 1883.29  536.751886.062   581.3  1896.6
   624.3 1897.53   658.8 1904.78   684.1 1905.77   714.7 1920.08   774.9 1916.91
   796.4 1919.26   851.2 1915.77   860.9  1920.3   878.1 1922.76     910  1942.1
#Mann= 7 ,-1,0
       0      .1       0     210    .025       0  324.94    .045       0
  536.75     .05       0     625     .03       0     735     .08       0
     845      .1       0
Bank Sta=324.94,536.75
XS Rating Curve= 0 ,0
Exp/Cntr=0.3,0.1

Type RM Length L Ch R = 1 ,38213   ,503.3,500,496.5
XS GIS Cut Line= 3
     2272227.779      705827.403     2272415.492      706241.695
     2272601.316       706657.36
#Sta/Elev= 30
       0 2054.12      59 2024.82    76.6 2013.89    94.2 2010.15   111.7 1995.18
   142.5 1974.62   164.8 1954.65     189  1938.6   225.9 1937.94   256.7 1931.97
   274.2 1926.44     305 1905.46   318.1 1898.49   344.5 1896.41   370.8 1897.31
  389.871884.594   398.3  1881.3   541.9 1881.51  552.171884.595     570 1894.74
   585.7 1895.61   625.1 1902.65   638.3 1902.92   673.3 1911.16   730.3 1907.65
   752.2 1909.62   804.8 1905.55   844.2 1923.83     888  1929.2   910.1 1928.47
#Mann= 7 ,-1,0
       0      .1       0     320    .025       0  389.87    .045       0
  552.17      .1       0  644.83     .08       0  864.83      .1       0
  884.83     .05       0
Bank Sta=389.87,552.17
XS Rating Curve= 0 ,0
Exp/Cntr=0.3,0.1

Type RM Length L Ch R = 1 ,37713   ,502.6,500,497.8
XS GIS Cut Line= 3
     2271763.404      706062.219     2271969.573      706467.829
     2272175.741      706873.439
#Sta/Elev= 30
       0 2089.27    48.2 2064.63    88.6 2035.82   115.5 2022.14   127.7  2010.9
   155.9 1997.45   169.3 1985.66   191.8 1970.79   222.4 1953.07     240 1936.72
   272.5 1912.92     277 1911.22   294.3 1910.05   308.4 1898.84   312.9 1896.73
   339.9 1894.24  371.911882.136   383.6 1877.54   496.1 1877.44  516.941882.134
   546.3 1894.92   582.2 1893.84   603.7 1895.37   631.5 1900.42   662.9 1901.14
   689.8 1907.74     793 1906.39     820 1903.88   842.4  1913.3     910 1924.21
#Mann= 6 ,-1,0
       0      .1       0  371.91    .045       0  516.94    .025       0
     525      .1       0     725     .08       0     835      .1       0
Bank Sta=371.91,516.94
XS Rating Curve= 0 ,0
Exp/Cntr=0.3,0.1

Type RM Length L Ch R = 1 ,37213   ,500,500,502.6
XS GIS Cut Line= 3
     2271305.251      706296.363     2271524.295      706695.167
     2271743.339      707093.971
#Sta/Elev= 30
       0 2108.64    19.2 2099.28    37.4 2097.58    82.3 2067.92    92.2 2058.84
   110.5 2052.91   142.4 2028.18   173.6 2011.26   251.9 1948.65   274.7 1945.68
   302.1 1921.13   346.7 1889.43   356.9  1883.2  372.79 1879.19   379.7 1876.16
   498.4 1876.16   512.9 1879.28  533.561879.192   577.2 1889.96   607.9 1890.41
   665.5 1898.28     692 1898.39   703.7  1903.2   715.6 1903.81   739.2  1911.3
   795.4 1910.41   821.7 1912.24   871.7 1909.85   886.8 1916.55     910 1918.55
#Mann= 5 ,-1,0
       0      .1       0     250    .025       0  372.79    .045       0
  533.56     .08       0     825      .1       0
Bank Sta=372.79,533.56
XS Rating Curve= 0 ,0
Exp/Cntr=0.3,0.1

Type RM Length L Ch R = 1 ,36713   ,502.8,500,506
XS GIS Cut Line= 3
     2270867.004      706537.071     2271086.049      706935.875
     2271305.093      707334.679
#Sta/Elev= 30
       0 2095.92      64 2063.91      96 2060.33   118.8  2049.4   151.2 2025.32
   164.4 2008.28   176.9 1996.03   189.5 1978.33   210.1 1974.55   236.6 1950.43
   283.7 1917.62   296.8 1911.18   313.2    1907   333.8 1889.29   357.4 1882.86
  369.311876.661     375 1874.76   570.6 1874.73     5821876.661   592.4 1879.59
   607.1 1887.37   648.2 1887.02     671 1893.23   722.6 1896.13     755 1908.28
   780.5 1917.74     817 1918.62   835.3 1916.72   858.2 1918.59     910 1916.17
#Mann= 6 ,-1,0
       0      .1       0     310    .025       0  369.31    .045       0
     582     .08       0     755     .07       0     875     .08       0
Bank Sta=369.31,582
XS Rating Curve= 0 ,0
Exp/Cntr=0.3,0.1

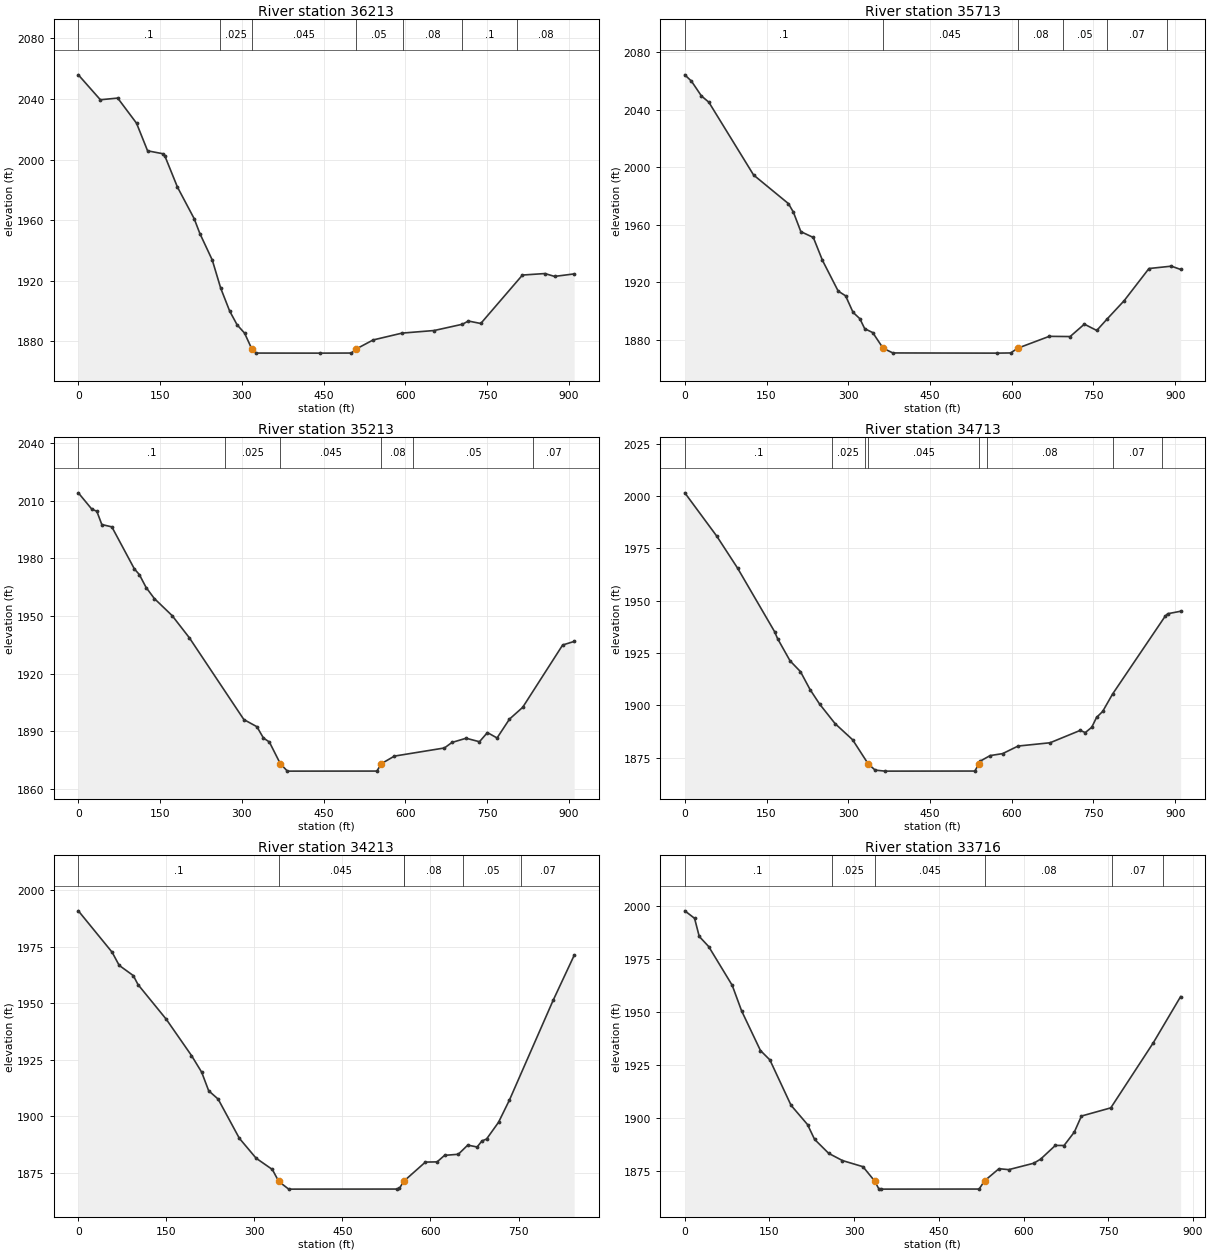
Type RM Length L Ch R = 1 ,36213   ,502.2,500,511.4
XS GIS Cut Line= 3
     2270428.758      706777.779     2270647.802      707176.583
     2270866.847      707575.387
#Sta/Elev= 30
       0 2055.98    40.4 2039.53    72.3 2040.62   106.8 2024.06   127.1 2005.82
   154.5 2003.94     159 2002.24   181.9 1981.87   212.6 1961.04   223.1 1951.18
   245.8 1933.74   261.3 1915.16   277.7 1900.08   291.4 1890.94   305.1 1885.48
  318.64 1874.82   326.1 1872.31   443.9 1872.27   501.3 1872.33  508.911874.818
   541.1 1880.97   594.2 1885.49   653.1  1887.2     705 1891.34   715.8 1893.46
   738.6 1891.83   815.1 1923.81   856.3  1924.8     874 1922.91     910 1924.56
#Mann= 7 ,-1,0
       0      .1       0     260    .025       0  318.64    .045       0
  508.91     .05       0     595     .08       0     705      .1       0
     805     .08       0
Bank Sta=318.64,508.91
XS Rating Curve= 0 ,0
Exp/Cntr=0.3,0.1

Type RM Length L Ch R = 1 ,35713   ,500.9,500,502.4
XS GIS Cut Line= 3
     2269990.512      707018.487     2270209.556      707417.291
       2270428.6      707816.095
#Sta/Elev= 30
       0 2064.24    12.2 2059.84    30.5 2049.55    44.1 2045.21   126.3 1994.53
   190.2 1974.64   199.3 1968.71     213 1955.15   235.9 1951.07   252.7 1935.13
   281.5 1913.79   295.1 1910.49   308.8    1899   321.3 1894.56   330.2 1887.62
   344.9 1884.91  364.02 1874.01   381.9 1870.75   573.5 1870.62   598.2 1870.75
  610.75 1874.01   668.9  1882.3   707.2 1882.15   733.3 1890.77   756.1 1886.39
     775 1894.33   806.3 1907.08   851.9 1929.48     893 1931.12     910 1928.84
#Mann= 6 ,-1,0
       0      .1       0  364.02    .045       0  610.75     .08       0
     695     .05       0     775     .07       0     885     .08       0
Bank Sta=364.02,610.75
XS Rating Curve= 0 ,0
Exp/Cntr=0.3,0.1

Type RM Length L Ch R = 1 ,35213   ,501.3,500,500.3
XS GIS Cut Line= 3
     2269547.179      707259.601     2269770.305      707656.135
     2269993.432       708052.67
#Sta/Elev= 30
       0 2014.06    24.8 2005.55    33.9 2004.49    43.1 1997.57    61.5 1996.36
   102.8 1974.54     112 1971.55   124.4 1964.84   139.5 1959.11   172.2 1950.22
   203.8 1938.69   303.8 1896.19   327.7 1892.48   339.7 1886.61   350.6 1884.52
  370.691873.261   383.7 1869.38     548 1869.41  556.121873.258   580.1 1877.19
   671.9 1881.42   685.7 1884.28   711.7 1886.48   736.2 1884.66   750.8 1889.43
   768.5 1886.62   791.3 1896.43   815.5 1902.53   888.9 1934.95     910  1936.8
#Mann= 6 ,-1,0
       0      .1       0     270    .025       0  370.69    .045       0
  556.12     .08       0     615     .05       0     835     .07       0
Bank Sta=370.69,556.12
XS Rating Curve= 0 ,0
Exp/Cntr=0.3,0.1

Type RM Length L Ch R = 1 ,34713   ,448.9,500,540.5
XS GIS Cut Line= 3
     2269111.427      707504.795     2269334.553      707901.329
      2269557.68      708297.864
#Sta/Elev= 30
       0  2001.6    58.6 1980.92    96.8 1965.63   164.7 1935.27   170.3  1931.9
   193.2 1921.28   212.3 1916.12   229.9 1907.56   247.5 1900.59   275.8 1891.28
     308 1883.56  336.361872.119   349.3 1869.04   367.6 1868.56   532.4  1868.6
  539.811872.123     542 1873.31   560.4 1875.99   583.3 1876.93   611.7 1880.55
   670.4 1882.12   725.6 1888.02   735.1 1886.99   746.9 1889.54   755.7 1894.23
   766.9 1897.09     785 1905.37   881.7 1942.64   886.3  1943.8     910 1944.99
#Mann= 8 ,-1,0
       0      .1       0     270    .025       0     330      .1       0
  336.36    .045       0  539.81      .1       0     555     .08       0
     785     .07       0     875     .08       0
Bank Sta=336.36,539.81
XS Rating Curve= 0 ,0
Exp/Cntr=0.3,0.1

Type RM Length L Ch R = 1 ,34213   ,475.3,496.9,517.7
XS GIS Cut Line= 3
     2268839.596      707631.756     2268875.725      708085.319
2268905.95023949708473.930634338
#Sta/Elev= 30
       0 1990.91    57.6  1972.6    69.6  1966.8    93.7 1962.27   101.7  1958.3
   149.9 1942.95   192.8 1926.94   210.1  1919.6   222.1 1911.36   238.2 1907.68
   274.3 1890.37   302.9 1881.55   330.5 1876.58  341.541871.272   358.4 1867.88
   543.1 1867.91   547.1 1868.17  554.091871.275   591.3 1879.83   611.3 1879.93
     624 1882.81   647.4 1883.29   663.5 1887.34   679.5 1886.51   687.6 1889.16
   695.6 1890.05   715.9 1897.41   734.5 1907.25   808.9  1951.3   844.8 1971.22
#Mann= 6 ,-1,0
       0      .1       0  341.54    .045       0  554.09    .025       0
     555     .08       0     655     .05       0     755     .07       0
Bank Sta=341.54,554.09
XS Rating Curve= 0 ,0
Exp/Cntr=0.3,0.1

Type RM Length L Ch R = 1 ,33716   ,441.3,503.1,557.2
XS GIS Cut Line= 4
2268475.00212822707644.6267041532268401.17528008707895.760466101
2268349.96674255708287.822386496     2268341.696      708508.797
#Sta/Elev= 30
       0 1997.85    17.3 1994.32    25.6 1985.77    42.3 1981.01      84 1962.72
   100.6 1950.69     134 1931.98   150.7 1927.56   188.2 1906.15   217.4 1897.07
   229.9 1890.09   254.9 1883.49   279.3 1880.09   315.6  1877.2  336.051870.537
   343.9 1866.66   347.9 1866.62   521.4 1866.66  530.951870.535   556.5 1876.25
   573.8 1875.81   618.2 1878.84   630.3 1880.77   656.4 1887.23   671.8 1887.19
     690 1893.53   702.6 1901.08   754.6 1904.94     830 1935.68   878.3 1957.41
#Mann= 6 ,-1,0
       0      .1       0     260    .025       0  336.05    .045       0
  530.95     .08       0  757.15     .07       0  847.15     .05       0
Bank Sta=336.05,530.95
XS Rating Curve= 0 ,0
Exp/Cntr=0.3,0.1