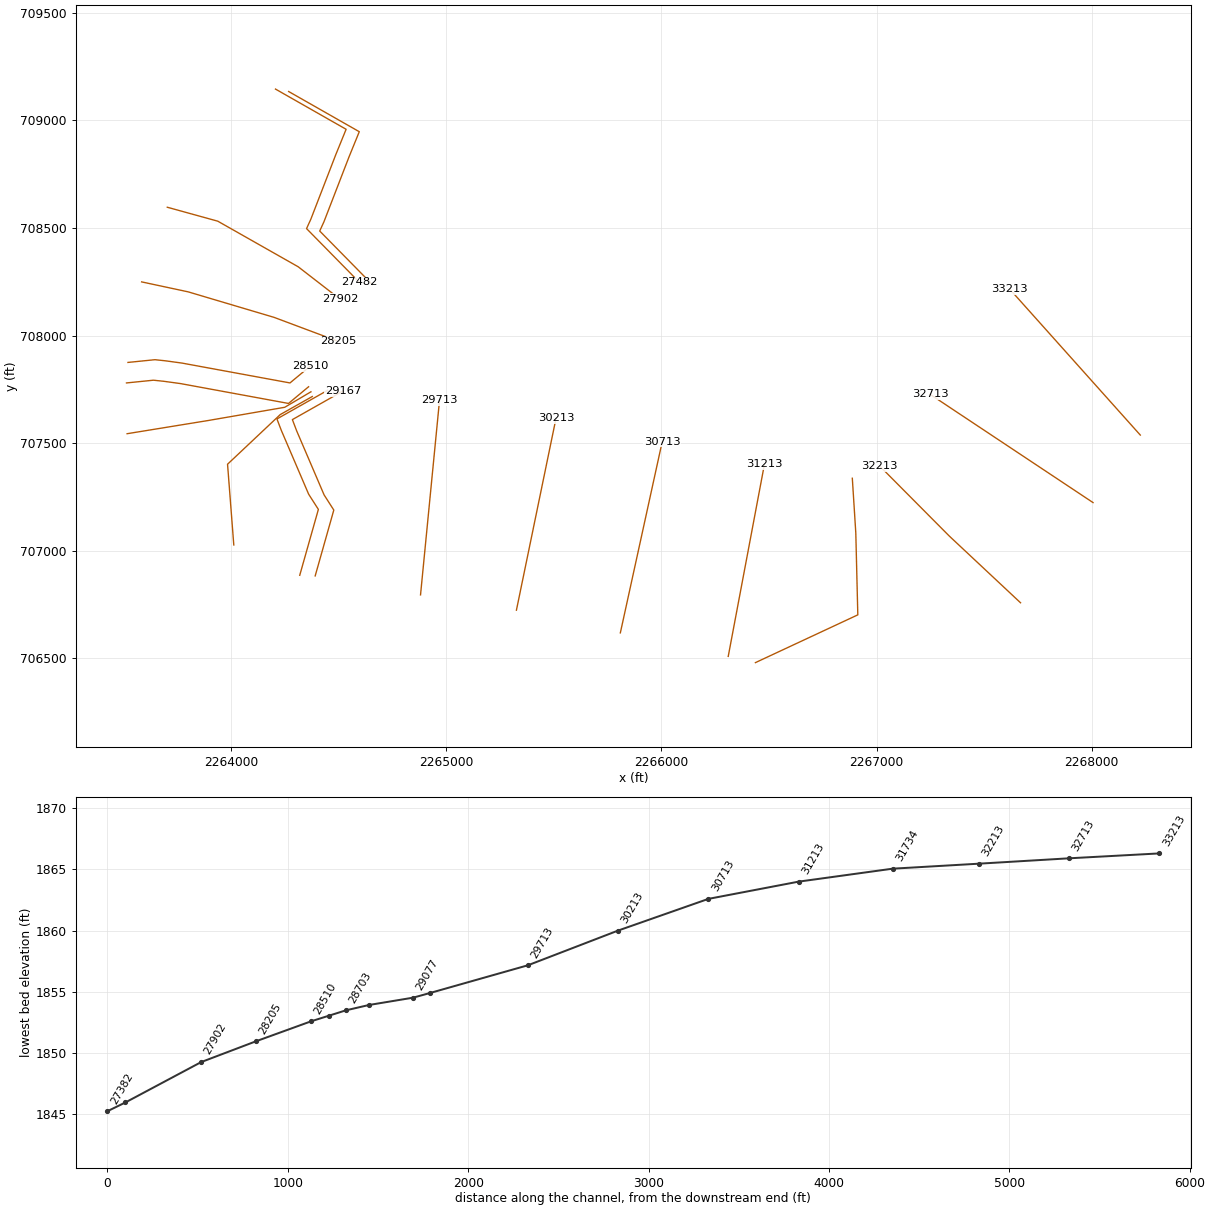
HEC-RAS study TYGVRV1.prj: TYGVRV1

--- TYGVRV1.g01 (geometry) --- (continued)

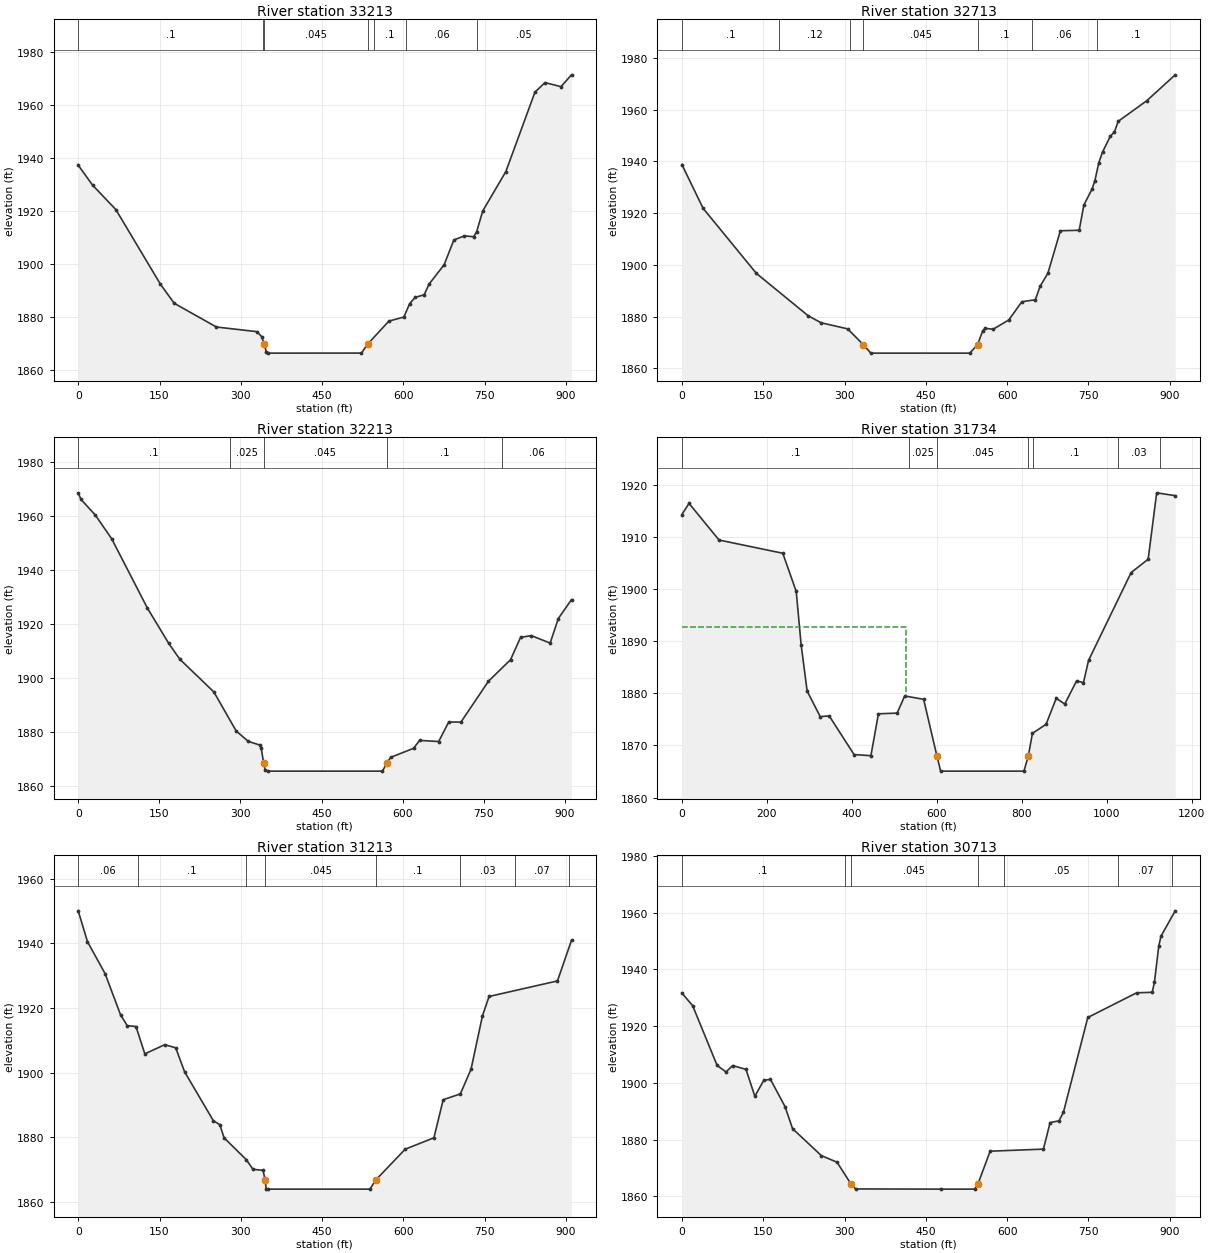
Type RM Length L Ch R = 1 ,33213   ,470.6,500,520.1
XS GIS Cut Line= 3
     2268226.171      707537.401      2267922.83      707876.531
     2267619.489      708215.662
#Sta/Elev= 30
       0 1937.34    26.5  1929.8    69.5 1920.55   151.4 1892.45     177 1885.16
     255 1876.18   329.9 1874.42   338.4 1872.54   343.11869.697   346.9 1866.85
     351 1866.31   522.5 1866.33  533.911869.697     573  1878.4   600.8 1879.96
   611.5 1885.04   621.6 1887.37   638.3 1888.38   647.1 1892.36     675 1899.71
     693 1909.08   712.3 1910.62   729.6 1910.31     735 1912.19   746.3 1920.07
   788.8 1934.89   842.6 1964.94     861 1968.55   890.6 1967.03     910 1971.49
#Mann= 7 ,-1,0
       0      .1       0     340    .025       0   343.1    .045       0
  533.91    .025       0     545      .1       0     605     .06       0
     735     .05       0
Bank Sta=343.1,533.91
XS Rating Curve= 0 ,0
Exp/Cntr=0.3,0.1

Type RM Length L Ch R = 1 ,32713   ,518.7,500,477.9
XS GIS Cut Line= 3
     2268006.498      707223.528     2267627.537      707475.348
     2267248.576      707727.168
#Sta/Elev= 30
       0 1938.77    39.1 1921.87   137.3 1896.74   233.3 1880.29   256.8 1877.64
   305.8 1875.28  334.611869.202   348.6 1865.91   531.1 1865.91  545.551869.201
   555.1 1874.65   559.5 1875.48   574.2 1875.14   603.1 1878.73   627.1 1885.76
   652.1 1886.54   660.7  1891.7   675.2 1896.79   698.2 1913.19   732.9 1913.37
   741.5  1923.1   756.8 1929.38   761.9 1932.57   769.1  1939.5     776 1943.62
   790.4 1949.73     798 1951.39   804.8 1955.45   857.7 1963.44     910 1973.43
#Mann= 7 ,-1,0
       0      .1       0     180     .12       0     310    .025       0
  334.61    .045       0  545.55      .1       0     645     .06       0
     765      .1       0
Bank Sta=334.61,545.55
XS Rating Curve= 0 ,0
Exp/Cntr=0.3,0.1

Type RM Length L Ch R = 1 ,32213   ,563.3,479.1,391.3
XS GIS Cut Line= 3
     2267669.463      706757.696      2267337.75      707068.379
     2267015.021      707393.193
#Sta/Elev= 30
       0  1968.5     5.1 1966.06    31.7 1960.27    62.1 1951.42     128 1925.82
   167.5 1912.74   188.1 1906.86   250.9 1894.79   292.2 1880.34   314.7 1876.46
   336.1 1875.12   338.6 1873.87  342.841868.581   345.8 1865.86   350.3 1865.47
   562.7 1865.47  571.331868.578   577.8 1870.56   620.2 1873.91   631.5 1876.85
   666.7 1876.43   685.3 1883.65   707.9 1883.62   758.8 1898.75   799.6 1906.71
   818.2 1914.99     838 1915.64   872.9 1912.88     888 1921.96   912.4 1928.97
#Mann= 5 ,-1,0
       0      .1       0     280    .025       0  342.84    .045       0
  571.33      .1       0  784.49     .06       0
Bank Sta=342.84,571.33
XS Rating Curve= 0 ,0
Exp/Cntr=0.3,0.1

Type RM Length L Ch R = 1 ,31734   ,542.9,520.9,498.1
XS GIS Cut Line= 4
2266436.98275705706479.4185469792266913.01644201706701.495705312
2266903.67885339707081.963952712 2266887.4754267      707336.695
#Sta/Elev= 30
       0 1914.27    16.8 1916.41    87.4 1909.38   237.5 1906.84   269.1 1899.52
   280.6 1889.34   294.8 1880.41   325.6 1875.51   346.8 1875.65   405.2 1868.24
   444.9 1868.02   462.6 1876.05   506.7 1876.19   524.4 1879.48     569 1878.83
  600.241867.975     609 1865.06   805.1 1865.06815.23991867.917   825.1 1872.31
   857.1 1874.03   881.1 1879.03   901.1 1877.93   929.1 1882.37   945.2 1882.03
   957.2  1886.3  1057.4 1903.14  1097.5  1905.7  1117.5 1918.43  1161.1 1917.89
#Mann= 7 ,-1,0
       0      .1       0  535.29    .025       0  600.24    .045       0
815.2399    .025       0  825.29      .1       0 1025.87     .03       0
 1125.87     .07       0
#XS Ineff= 2 , 0
          527.65 1892.66
Permanent Ineff=
       F       F
Bank Sta=600.24,815.2399
XS Rating Curve= 0 ,0
Exp/Cntr=0.3,0.1

Type RM Length L Ch R = 1 ,31213   ,504.4,500,497.2
XS GIS Cut Line= 3
      2266310.65      706508.384     2266394.907      706955.515
     2266479.163      707402.645
#Sta/Elev= 30
       0 1950.08    17.1 1940.53    49.7 1930.62    78.1 1917.92    90.4 1914.56
   106.6  1914.3   122.9 1905.83   159.6 1908.68   179.9 1907.71   196.2 1900.31
   249.1 1885.22   261.3  1883.9   269.1 1879.87     310 1873.12   322.4 1870.13
   341.1 1869.81   344.7 1866.86   346.8 1864.11   350.9    1864   538.1    1864
  549.061866.858   603.2 1876.35   656.2 1879.88   673.3 1891.65     705 1893.46
   724.7 1901.11   745.7 1917.57   757.9 1923.59   884.1  1928.4     910 1940.97
#Mann= 8 ,-1,0
       0     .06       0     110      .1       0     310    .025       0
   344.7    .045       0  549.06      .1       0     705     .03       0
     805     .07       0     905      .1       0
Bank Sta=344.7,549.06
XS Rating Curve= 0 ,0
Exp/Cntr=0.3,0.1

Type RM Length L Ch R = 1 ,30713   ,499.2,500,501.2
XS GIS Cut Line= 3
     2265809.078        706617.7     2265906.419      707062.166
     2266003.759      707506.632
#Sta/Elev= 30
       0 1931.69    19.9 1927.19      65 1906.16    81.4 1903.88    93.6 1906.12
   118.2 1904.77   134.6 1895.31     151 1900.88   163.3 1901.28   190.3 1891.65
   204.2 1883.88   257.4 1874.38   286.1 1872.09  311.551864.517   320.3 1862.66
   478.6 1862.59     540 1862.59  546.41 1864.52   568.6 1875.96   666.9 1876.68
   679.2 1886.02   695.6 1886.65   703.8 1889.64   748.8 1923.06   838.9 1931.75
   867.6 1931.93   871.7 1935.46   879.8 1948.38   883.9 1951.72     910 1960.63
#Mann= 7 ,-1,0
       0      .1       0     300    .025       0  311.55    .045       0
  546.41      .1       0     595     .05       0     805     .07       0
     905      .1       0
Bank Sta=311.55,546.41
XS Rating Curve= 0 ,0
Exp/Cntr=0.3,0.1

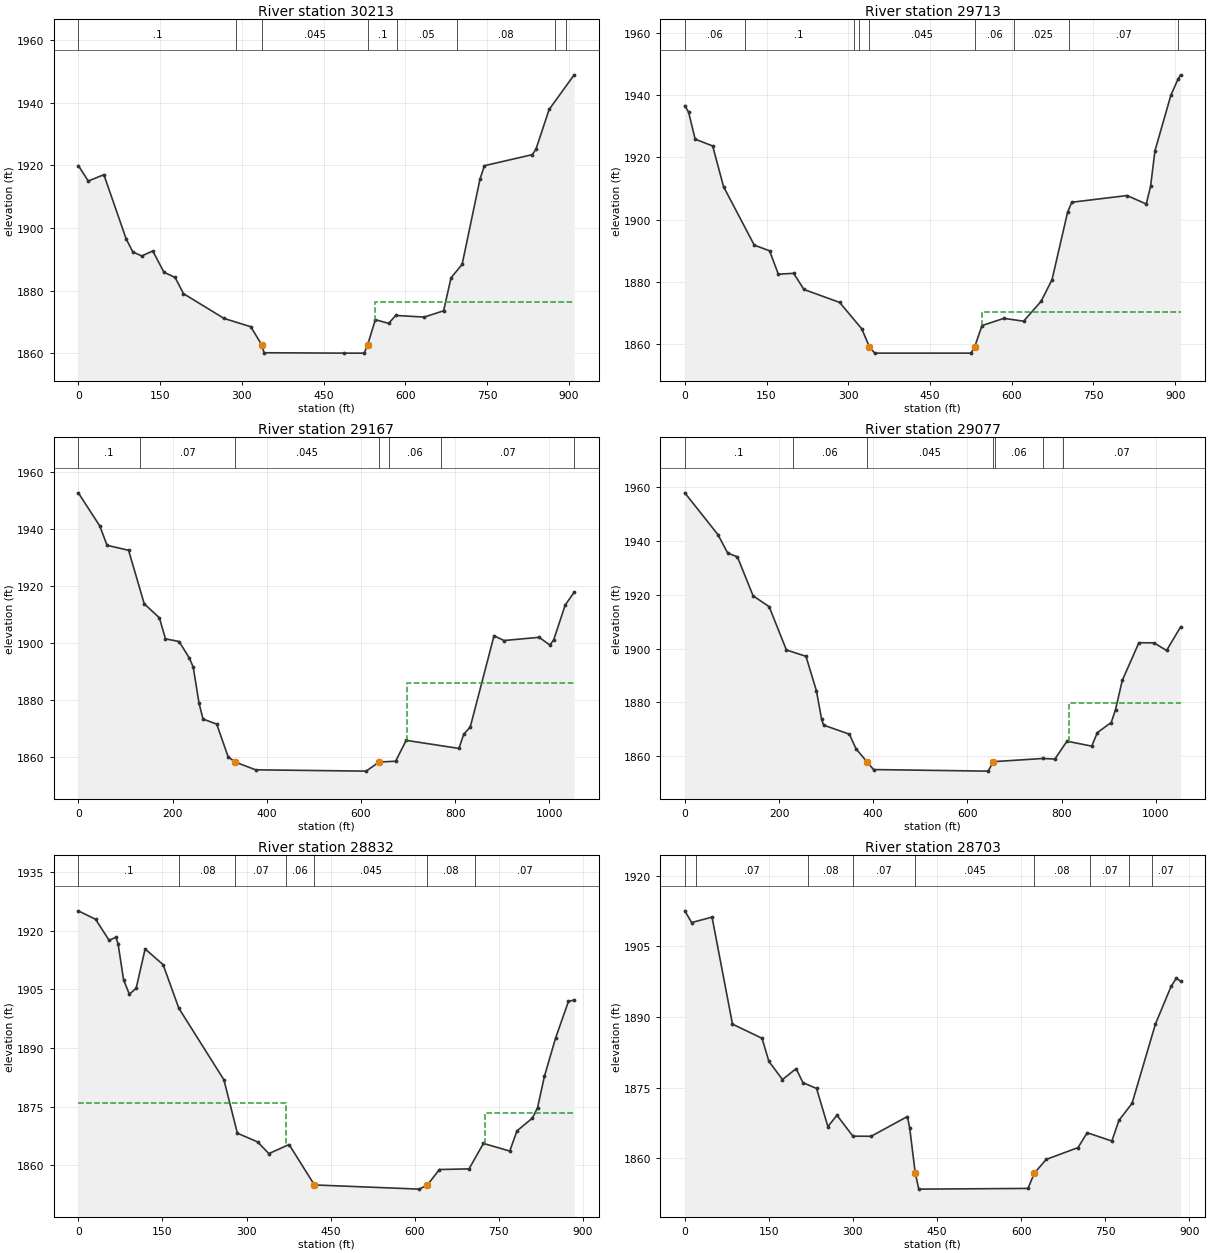
Type RM Length L Ch R = 1 ,30213   ,487.4,500,508.1
XS GIS Cut Line= 3
     2265326.031       706723.28     2265417.945        707168.9
     2265509.859      707614.519
#Sta/Elev= 30
       0 1919.94    18.3 1914.99    46.9 1917.02    87.7 1896.53     100 1892.35
   116.3 1891.05   136.7 1892.64   157.1 1885.85   177.6 1884.18     193 1879.01
   267.4 1871.09   316.4 1868.44  336.661862.654   340.9 1860.12   487.6    1860
   524.7    1860  530.981862.656   545.1 1870.69   569.6  1869.5   582.4 1872.04
     635 1871.52   670.4 1873.53     684 1884.04   704.4 1888.37   737.1 1915.55
   745.3 1919.89     833 1923.42   839.7 1925.07   864.1 1937.87     910 1948.93
#Mann= 8 ,-1,0
       0      .1       0     290    .025       0  336.66    .045       0
  530.98      .1       0     585     .05       0     695     .08       0
     875     .07       0     895      .1       0
#XS Ineff= 2 , 0
                          544.43         1876.25
Permanent Ineff=
       F       F
Bank Sta=336.66,530.98
XS Rating Curve= 0 ,0
Exp/Cntr=0.3,0.1

Type RM Length L Ch R = 1 ,29713   ,450.9,545.5,614.8
XS GIS Cut Line= 3
     2264880.249      706794.318     2264924.455      707247.166
     2264968.661      707700.013
#Sta/Elev= 30
       0 1936.62     6.9 1934.61      19 1925.89    51.1 1923.71    71.2  1910.6
   127.5 1891.85   155.6 1890.03   171.7 1882.52   199.8 1882.79   218.6 1877.62
   284.2 1873.44   324.8 1864.96  338.571859.266   348.5 1857.16   525.3 1857.16
  532.161859.262   545.4    1866   585.6 1868.33   621.8 1867.41     654 1873.82
     674 1880.76   702.5 1902.37   710.2 1905.62   811.8 1907.78   846.9 1905.05
   854.9 1910.79   862.9 1922.16   892.3 1940.11     905 1945.06     910 1946.55
#Mann= 9 ,-1,0
       0     .06       0     110      .1       0     310    .025       0
     320     .06       0  338.57    .045       0  532.16     .06       0
     605    .025       0     705     .07       0     905     .06       0
#XS Ineff= 2 , 0
                          545.66         1870.42
Permanent Ineff=
       F       F
Bank Sta=338.57,532.16
XS Rating Curve= 0 ,0
Exp/Cntr=0.3,0.1

Type RM Length L Ch R = 1 ,29167   ,111.3,90.9,80.6
XS GIS Cut Line= 6
2264390.51927099 706882.514059232264477.12564947707188.743936038
2264431.94047675707259.3419356222264304.41807113707557.128783288
2264284.51573184707609.2866379862264520.21199299707742.489902162
#Sta/Elev= 30
       0 1952.58    45.6 1940.93      61 1934.15   106.7 1932.41   139.9 1913.63
     172 1908.72     185 1901.33   214.1 1900.37   235.6 1894.59   243.9 1891.42
   256.3  1878.7   264.7 1873.17   293.8 1871.38   318.2 1859.84  333.09 1858.07
   376.4 1855.34     611 1854.88  638.48 1858.07   673.7 1858.36     696 1865.69
     808 1862.85   818.3 1867.84   832.1 1870.38   882.6 1902.42   903.7 1900.73
   978.3 1901.86  1001.2 1899.14  1009.3 1900.98  1033.7  1913.2  1052.7 1917.68
#Mann= 7 ,-1,0
       0      .1       0     130     .07       0  333.09    .045       0
  638.48    .025       0  659.45     .06       0     770     .07       0
 1051.92     .06       0
#XS Ineff= 2 , 0
                          698.34          1885.8
Permanent Ineff=
       F       F
Bank Sta=333.09,638.48
XS Rating Curve= 0 ,0
Exp/Cntr=0.3,0.1

Type RM Length L Ch R = 1 ,29077   ,400.3,244.8,124.8
XS GIS Cut Line= 6
 2264318.7838633706885.6207107442264405.39024178707191.850587552
2264360.20506906707262.4485871362264232.68266343707560.235434803
2264212.78032414707612.393289501 2264448.4765853707745.596553677
#Sta/Elev= 30
       0 1957.76    70.2 1942.29      91 1935.44   111.8 1933.97     145 1919.54
     179 1915.54   215.7 1899.47   257.3  1897.1   279.4 1884.34   290.5 1873.75
   294.7 1871.57   349.5 1868.22   363.4 1862.83   386.6 1858.02   386.6 1858.01
   400.7 1855.09   644.1 1854.51  655.18 1858.02     760  1859.2   785.8    1859
   811.4 1865.62   863.9 1863.78     876 1868.83   905.4 1872.55   914.5 1877.35
   928.8 1888.15   964.1 1902.15   996.4  1902.1  1022.8 1899.27  1052.7 1908.04
#Mann= 7 ,-1,0
       0      .1       0     230     .06       0   386.6    .045       0
  655.18    .025       0  659.45     .06       0     760     .08       0
  801.92     .07       0
#XS Ineff= 2 , 0
                          815.31         1879.76
Permanent Ineff=
       F       F
Bank Sta=386.6,655.18
XS Rating Curve= 0 ,0
Exp/Cntr=0.3,0.1

Type RM Length L Ch R = 1 ,28832   ,201.1,128.5,81.9
XS GIS Cut Line= 4
2264012.17479689707026.4625543292263983.15917627707401.916895986
2264228.05630932707632.635897085 2264377.0749461707716.659586996
#Sta/Elev= 30
       0 1925.03    30.8 1922.86    54.9 1917.49    66.9 1918.27    70.9 1916.58
    80.7 1907.38      91 1903.71   103.1 1905.24   119.1 1915.29   151.2 1911.26
   179.2 1900.14   259.6 1881.84   283.6  1868.2   319.7 1865.97   339.7 1862.98
   375.8 1865.31420.95651854.981     608 1853.91  622.41 1854.98   643.8 1858.92
   696.7 1859.09   722.3 1865.59   769.3 1863.64   782.1 1868.79   809.6 1872.05
   818.8  1874.7     831 1882.71   850.9 1892.48   873.9 1901.87   884.1 1902.25
#Mann= 7 ,-1,0
       0      .1       0     180     .08       0     280     .07       0
     370     .06       0420.9565    .045       0  622.41     .08       0
  706.57     .07       0
#XS Ineff= 2 , 0
          369.68 1876.04  724.91         1873.31
Permanent Ineff=
       F       F
Bank Sta=420.9565,622.41
XS Rating Curve= 0 ,0
Exp/Cntr(USF)=0,0
Exp/Cntr=0.3,0.1

Type RM Length L Ch R = 1 ,28703   ,162.8,94.4,69
XS GIS Cut Line= 4
2263516.16086305707543.7205344982263893.61917271707605.153354666
2264249.07203443707666.6148582082264370.87018987707738.557187724
#Sta/Elev= 30
       0 1912.56    12.2 1910.07    48.6 1911.22    85.1  1888.5   137.8  1885.5
     150  1880.6   174.3 1876.73   198.6 1879.05   210.8 1876.08   235.1 1874.84
   255.3 1866.76   271.5 1869.15   299.9 1864.72   332.4 1864.69   397.2 1868.89
   401.3 1866.41  411.181856.839   417.5 1853.47   612.3 1853.62  623.511856.841
   644.8 1859.78   701.6 1862.29   717.9 1865.45   761.9 1863.68   774.6 1868.08
   797.9 1871.67   839.7 1888.54   867.5  1896.5   876.8 1898.23   884.6 1897.62
#Mann= 9 ,-1,0
       0     .06       0      20     .07       0     220     .08       0
     300     .07       0  411.18    .045       0  623.51     .08       0
  722.42     .07       0  793.15     .08       0  833.15     .07       0
Bank Sta=411.18,623.51
XS Rating Curve= 0 ,0
Exp/Cntr(USF)=0,0
Exp/Cntr=0.3,0.1

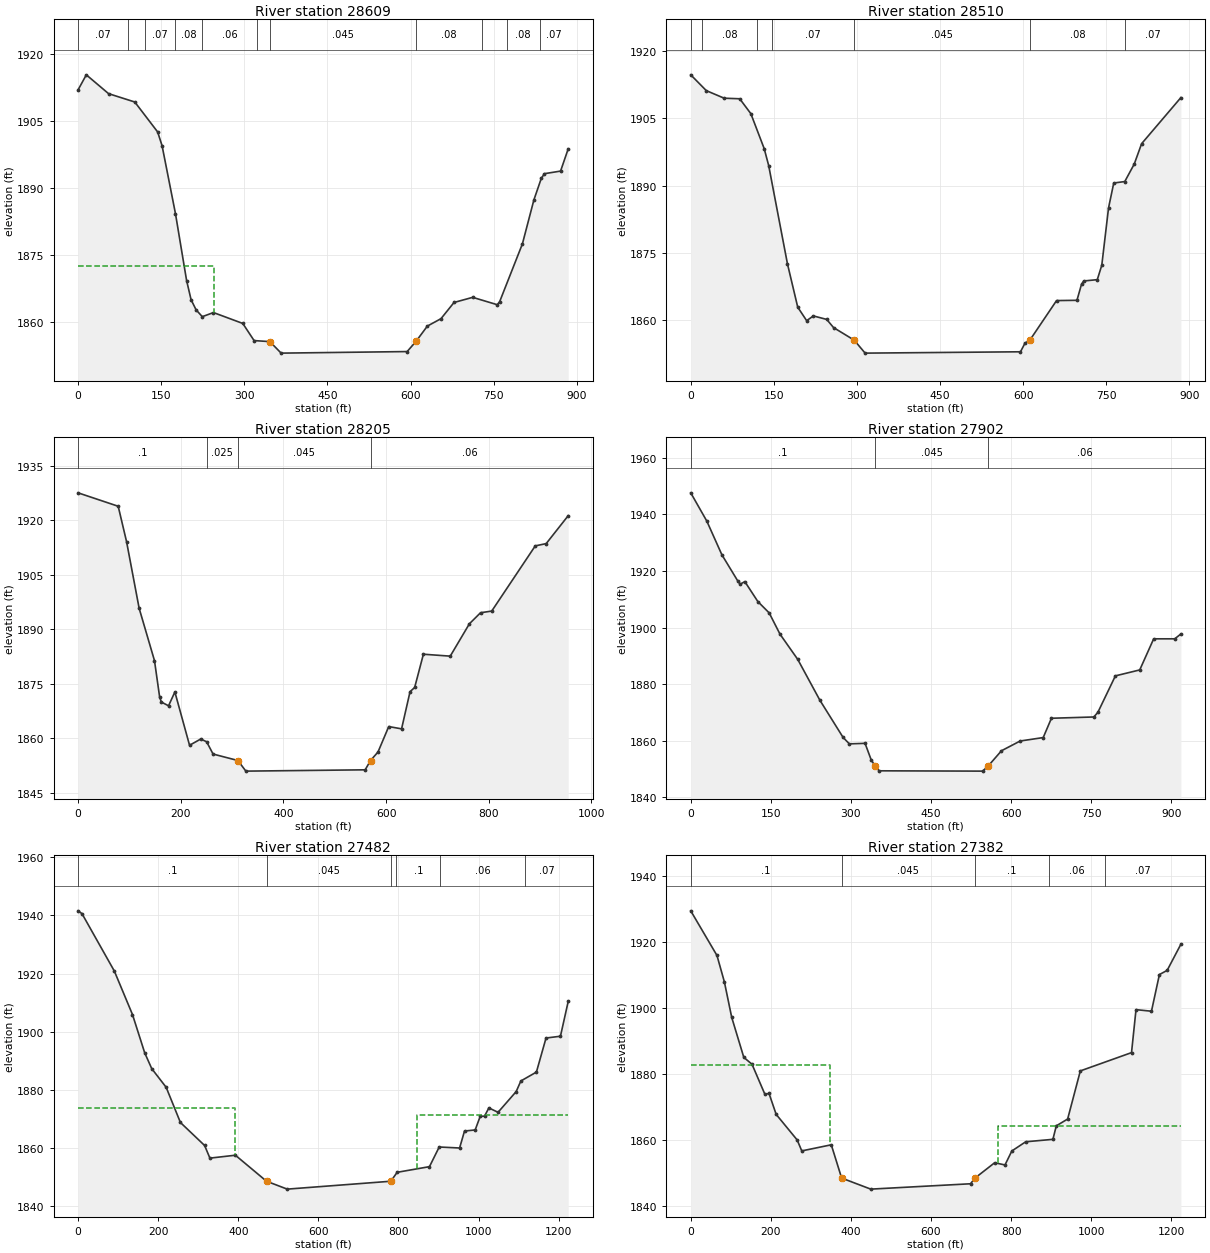
Type RM Length L Ch R = 1 ,28609   ,113.7,98.9,95.6
XS GIS Cut Line= 6
 2263513.3399638707779.809428083 2263638.7254158707792.498723513
2263687.00342249707787.410412957 2263764.7826795707776.734828662
2264266.53514136707684.4672786842264359.82707028 707762.01432564
#Sta/Elev= 30
       0 1912.01    14.9 1915.39    55.1 1911.17   102.4  1909.3   143.6  1902.6
   151.6 1899.53   175.8 1884.29   195.9  1869.3     204 1864.99   213.1 1862.72
   224.2  1861.2   244.4 1862.12   297.3 1859.68   317.7 1855.84   346.2 1855.61
   366.5 1853.03   593.9 1853.38   609.8 1855.64   630.4 1859.09     655 1860.75
   678.5 1864.38   712.2 1865.53   756.5 1863.88   760.9 1864.57   801.9  1877.5
   822.7 1887.38     836 1892.18   841.7 1893.24   870.8 1893.82   884.6 1898.81
#Mann= 11 ,-1,0
       0     .07       0      90     .08       0     120     .07       0
  174.57     .08       0  224.57     .06       0  323.08     .08       0
   346.2    .045       0   609.8     .08       0  729.35     .07       0
  773.32     .08       0  833.32     .07       0
#XS Ineff= 2 , 0
          244.77 1872.57
Permanent Ineff=
       F       F
Bank Sta=346.2,609.8
XS Rating Curve= 0 ,0
Exp/Cntr=0.3,0.1

Type RM Length L Ch R = 1 ,28510   ,322.4,304.7,295.8
XS GIS Cut Line= 6
2263520.20283942707875.1271450022263645.58829142707887.816440432
2263693.86629811707882.7281298762263771.64555512707872.052545581
2264273.39801698707779.784995603 2264366.6899459 707857.33204256
#Sta/Elev= 30
       0 1914.74    28.1 1911.21    60.3 1909.52    88.4 1909.39   108.5 1906.06
   132.6 1898.24   140.7 1894.45   174.6 1872.48   193.1 1862.83   209.2 1859.82
   221.3 1860.88   245.4  1860.1   257.7 1858.28  294.971855.472   314.7 1852.57
   595.1 1852.87   603.2 1854.79  612.021855.472   660.2 1864.31     697 1864.37
   705.2 1867.94   709.2 1868.69   733.7 1868.98   741.8  1872.2     754 1885.01
   763.4 1890.57   783.3  1890.9   800.4 1894.81   813.7 1899.36   884.6 1909.66
#Mann= 7 ,-1,0
       0     .07       0      20     .08       0     120     .06       0
  146.03     .07       0  294.97    .045       0  612.02     .08       0
  783.32     .07       0
Bank Sta=294.97,612.02
XS Rating Curve= 0 ,0
Exp/Cntr=0.3,0.1

Type RM Length L Ch R = 1 ,28205   ,335.7,303.4,284.5
XS GIS Cut Line= 4
2263583.78727713708249.5701834852263799.93821101708203.317850431
2264199.51498716708084.6411767972264496.37701882707973.532799768
#Sta/Elev= 30
       0 1927.57    78.2 1923.87    94.5 1914.12     119 1895.78   148.9 1881.36
     159 1871.27   162.4 1869.95   176.3 1868.93   188.6 1872.74   217.2 1858.06
     239 1859.78   250.5 1859.02     263 1855.64  311.361853.863   326.9 1850.94
   559.3  1851.3  569.731853.863   584.3 1856.21   605.2 1863.21   630.2 1862.58
   646.7 1872.82   655.7 1873.97   672.7 1883.13     725  1882.6   762.3 1891.51
     784 1894.55   805.8 1895.01   890.6 1912.96   911.9 1913.59   954.8 1921.28
#Mann= 4 ,-1,0
       0      .1       0  251.04    .025       0  311.36    .045       0
  569.73     .06       0
Bank Sta=311.36,569.73
XS Rating Curve= 0 ,0
Exp/Cntr=0.3,0.1

Type RM Length L Ch R = 1 ,27902   ,621.1,419.7,273.5
XS GIS Cut Line= 4
  2263703.027679708596.7028335482263937.83175135708531.797362028
2264311.58110501708319.854996063 2264505.1334467708170.005485296
#Sta/Elev= 30
       0 1947.66    30.2 1937.63    58.3 1925.76    88.3 1916.43    92.5 1915.33
   101.3 1916.27   125.7 1909.21   146.9  1905.2   167.2 1897.68   200.4 1888.76
   241.9 1874.31   285.4 1861.15   297.1 1858.88   326.5 1859.07   338.1 1853.17
  345.511851.027   352.9 1849.35   546.6 1849.24     5571851.026     582 1856.44
     617 1859.89   660.2 1861.11   675.6 1867.94     755 1868.39   762.6 1870.04
   795.4 1882.93     841 1885.03   867.1 1896.03   906.6 1896.03   918.1 1897.76
#Mann= 3 ,-1,0
       0      .1       0  345.51    .045       0     557     .06       0
Bank Sta=345.51,557
XS Rating Curve= 0 ,0
Exp/Cntr=0.3,0.1

Type RM Length L Ch R = 1 ,27482   ,121.4,100.2,103.2
XS GIS Cut Line= 6
2264206.03825973709146.0136265432264534.33267905708959.139530624
2264486.48977091708841.6387164932264370.26978713708540.814928688
2264350.44370201708497.3500497732264595.03420166708248.509055047
#Sta/Elev= 30
       0 1941.55     9.8 1940.59    90.6 1920.86   135.9 1905.92   166.4 1892.77
     184 1887.33     220 1880.92   255.6 1868.83     316 1860.93   329.2 1856.59
   392.8 1857.59  470.581848.651   522.3 1845.94  780.87 1848.65   796.7 1851.72
   877.4 1853.66   901.7 1860.41   952.6 1860.07   964.9  1865.9   991.5 1866.27
  1004.1 1870.96  1014.8 1870.99  1025.7 1873.84  1048.6 1872.33  1093.9 1879.46
  1105.6  1883.1  1144.4 1886.15  1168.4 1897.85  1204.4 1898.47  1223.8 1910.44
#Mann= 6 ,-1,0
       0      .1       0  470.58    .045       0  780.87    .025       0
  794.11      .1       0   904.9     .06       0  1114.9     .07       0
#XS Ineff= 2 , 0
          391.26 1873.95  845.95         1871.32
Permanent Ineff=
       F       F
Bank Sta=470.58,780.87
XS Rating Curve= 0 ,0
Exp/Cntr=0.3,0.1

Type RM Length L Ch R = 1 ,27382   ,431.4,650.6,794.2
XS GIS Cut Line= 6
2264267.22988047709134.7167119452264595.52429979708947.842616027
2264547.68139165708830.3418018952264431.46140787 708529.51801409
2264411.63532275708486.053135175 2264656.2258224 708237.21214045
#Sta/Elev= 30
       0  1929.4    65.5 1915.89      84  1907.9   102.3 1897.17   132.5 1885.07
     153 1882.99   185.2 1873.89   195.4 1874.18   213.3 1867.83   265.8 1860.08
   277.2 1856.78   350.9 1858.63  376.751848.562   449.5 1845.22   698.5 1846.84
  709.731848.564   758.8  1853.2   784.6 1852.53   801.7 1856.76   836.3 1859.54
   904.2 1860.28   912.7 1864.36     941 1866.42   972.7 1880.98  1100.5 1886.51
  1111.7 1899.51  1150.3 1899.03  1170.1 1910.12  1189.5 1911.39  1223.8 1919.31
#Mann= 5 ,-1,0
       0      .1       0  376.75    .045       0  709.73      .1       0
   894.9     .06       0  1034.9     .07       0
#XS Ineff= 2 , 0
          346.71  1882.9  766.21         1864.26
Permanent Ineff=
       F       F
Bank Sta=376.75,709.73
XS Rating Curve= 0 ,0
Exp/Cntr=0.3,0.1