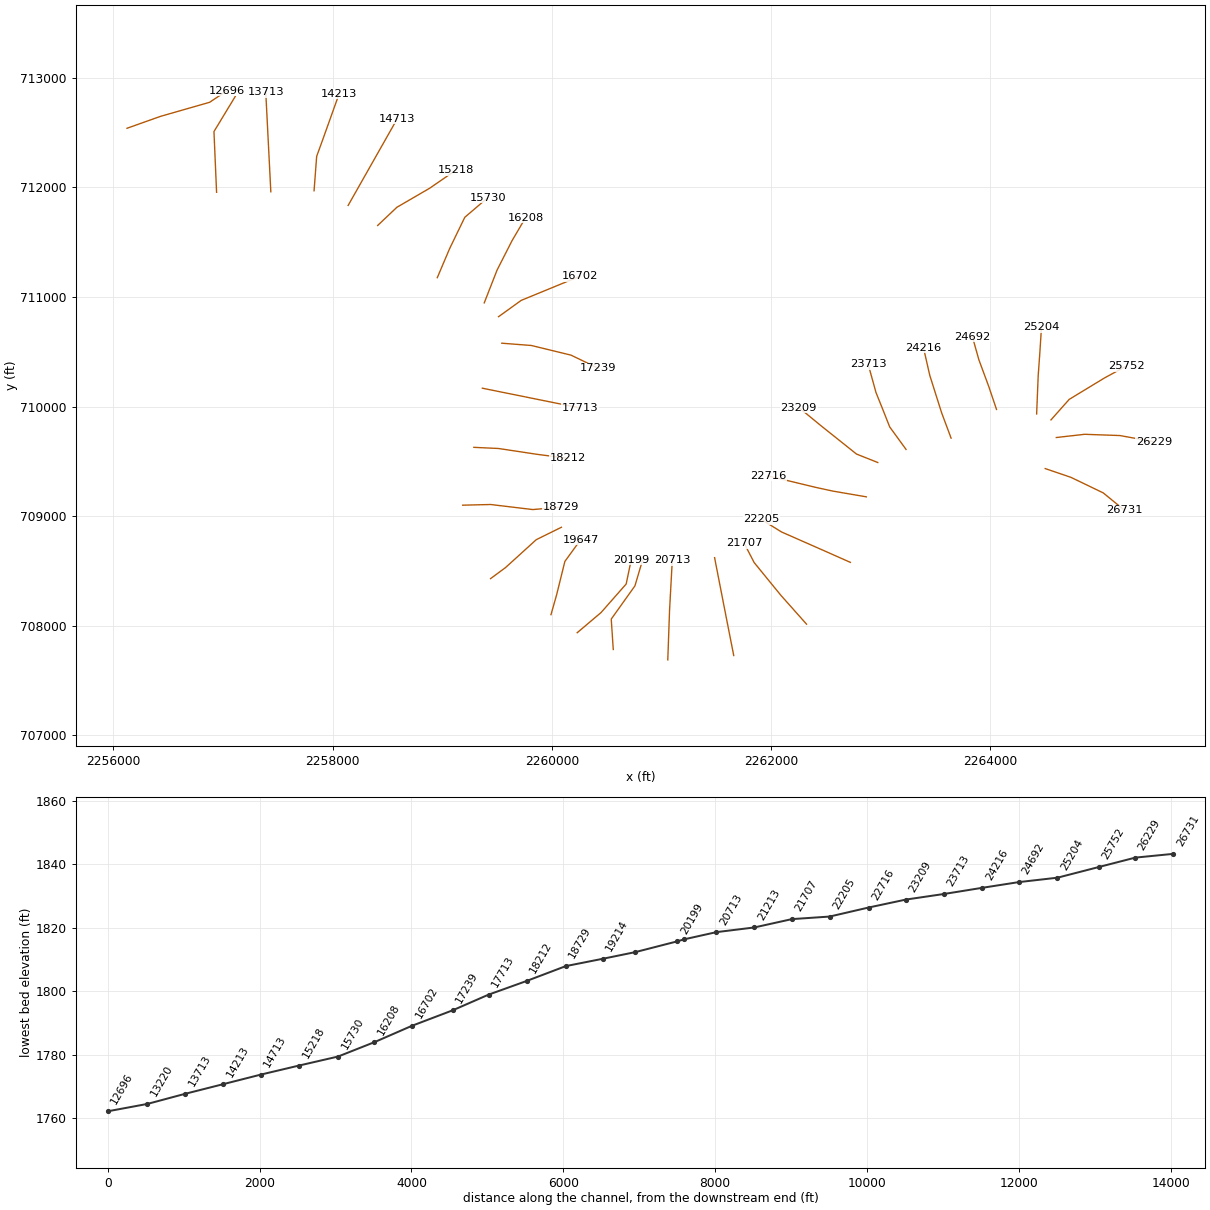
HEC-RAS study TYGVRV1.prj: TYGVRV1

--- TYGVRV1.g01 (geometry) --- (continued)

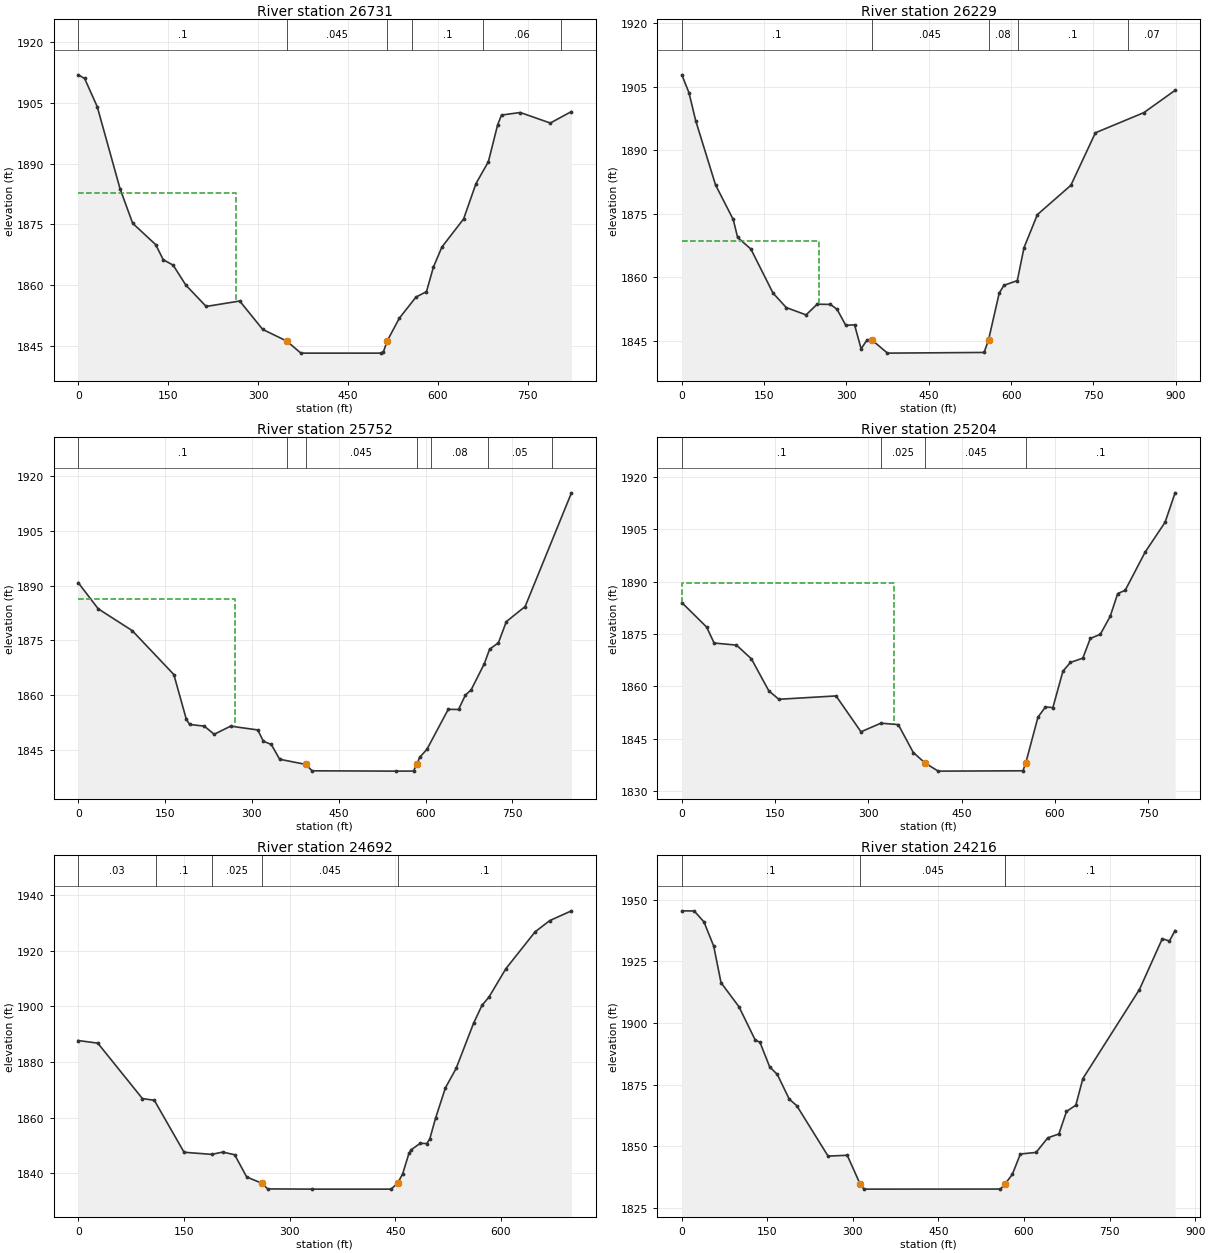
Type RM Length L Ch R = 1 ,26731   ,458.1,502.5,539.6
XS GIS Cut Line= 4
2264502.08370444709435.100071249 2264736.1920455709355.407297243
2265031.29310325709213.4043211872265223.49570078709056.353080663
#Sta/Elev= 30
       0 1911.94    10.7 1911.04    31.8 1904.06    69.8 1883.83    90.9  1875.3
   129.3 1870.02   141.9 1866.31   158.5 1864.95   179.6 1860.04   213.5 1854.77
   269.5 1856.11   307.8 1849.11   347.9 1846.23   371.6 1843.25   504.7 1843.25
   509.2 1843.56   515.7  1846.3   535.8 1851.87   563.6 1857.09   581.1 1858.42
   592.6 1864.46   606.8 1869.43   643.1 1876.38   663.7  1885.1   684.4  1890.5
   699.9 1899.63   706.3 1902.01   737.6 1902.64   787.7 1900.04     823 1902.88
#Mann= 6 ,-1,0
       0      .1       0   347.9    .045       0   515.7    .025       0
   557.3      .1       0  674.79     .06       0  804.79     .07       0
#XS Ineff= 2 , 0
          263.54 1882.72
Permanent Ineff=
       F       F
Bank Sta=347.9,515.7
XS Rating Curve= 0 ,0
Exp/Cntr=0.3,0.1

Type RM Length L Ch R = 1 ,26229   ,412.8,476.9,530.7
XS GIS Cut Line= 4
2264603.16742959709718.6287183392264862.02404729 709747.91285917
2265183.73480399709736.4531182172265495.04714792709680.149882813
#Sta/Elev= 30
       0 1907.79    13.1 1903.53    25.2 1896.98    61.4  1881.8    93.6 1873.63
   101.7 1869.38   125.8 1866.65   166.2 1856.24   190.2 1852.83   226.4 1851.09
   246.6 1853.62   270.7 1853.56   282.7 1852.44   298.7 1848.63   314.7 1848.75
   326.7 1843.08   337.3 1845.14   346.7 1845.13   374.7 1842.06   550.8 1842.22
   558.91845.205   578.3 1856.23   586.9 1858.07   611.3 1859.19   623.5 1866.97
   647.9 1874.78   708.9  1881.7   753.6  1894.1   841.9 1898.86   898.8 1904.13
#Mann= 5 ,-1,0
       0      .1       0   346.7    .045       0   558.9     .08       0
  612.42      .1       0  812.42     .07       0
#XS Ineff= 2 , 0
          249.82 1868.58
Permanent Ineff=
       F       F
Bank Sta=346.7,558.9
XS Rating Curve= 0 ,0
Exp/Cntr=0.3,0.1

Type RM Length L Ch R = 1 ,25752   ,459.5,547.5,632.4
XS GIS Cut Line= 4
     2264554.415      709879.3412264720.67719928 710066.43666724
2265043.24509922710262.2768796362265240.45391763710369.449031918
#Sta/Elev= 30
       0 1890.84    34.6 1883.65    93.4 1877.66   165.2 1865.63   186.7  1853.4
   192.4 1851.93   217.9 1851.46   234.9 1849.23   263.3 1851.46   310.2 1850.42
   319.9 1847.32   333.5 1846.45     348 1842.38  392.941840.963   404.1 1839.21
   548.9 1839.12   579.3 1839.14  584.761840.962   589.7 1842.87   602.4  1845.1
   639.3 1856.09     657 1856.03   668.8 1859.96   678.8 1861.43   701.6  1868.6
   710.7 1872.58   725.9 1874.33   739.6 1880.14   772.1 1884.29   852.1 1915.48
#Mann= 7 ,-1,0
       0      .1       0   360.3    .025       0  392.94    .045       0
  584.76    .025       0   610.3     .08       0  707.66     .05       0
  817.66     .08       0
#XS Ineff= 2 , 0
          270.04 1886.27
Permanent Ineff=
       F       F
Bank Sta=392.94,584.76
XS Rating Curve= 0 ,0
Exp/Cntr=0.3,0.1

Type RM Length L Ch R = 1 ,25204   ,480.7,512.1,554.1
XS GIS Cut Line= 4
     2264423.674      709933.3542264437.82663242710281.134940091
2264454.22292897710511.1328091942264467.82258227710725.253252514
#Sta/Elev= 30
       0 1884.04    39.9 1877.02    51.9 1872.45    87.9 1871.85   111.9 1867.91
   139.9 1858.74     156 1856.33     248 1857.29   288.1 1847.01   320.1 1849.48
   348.1 1849.07   372.2 1841.07   391.5 1838.02   412.3 1835.74   548.6 1835.84
  553.161838.144   572.7  1851.2   584.7 1854.12   596.7 1853.95   612.8 1864.36
   624.8 1866.88   644.8 1868.11   656.9 1873.77   672.9 1874.93   688.9 1880.12
   700.9 1886.62     713 1887.56     745 1898.49   777.1 1907.05   793.2 1915.49
#Mann= 4 ,-1,0
       0      .1       0     320    .025       0   391.5    .045       0
  553.16      .1       0
#XS Ineff= 2 , 0
          341.95 1889.53
Permanent Ineff=
       F       F
Bank Sta=391.5,553.16
XS Rating Curve= 0 ,0
Exp/Cntr=0.3,0.1

Type RM Length L Ch R = 1 ,24692   ,486.2,476.7,471.5
XS GIS Cut Line= 4
2264057.58015216709974.8793153472263988.69842249710179.013887541
2263896.62386261 710427.993513742263837.30185562710638.779938909
#Sta/Elev= 30
       0 1887.74    27.8  1886.8    91.1 1866.89     108 1866.26   150.2 1847.59
   189.2 1846.83   205.1 1847.65     222  1846.7   239.1 1838.69  260.651836.456
   268.9 1834.42   332.3 1834.34   443.8 1834.34  453.271836.457   460.4 1839.84
   469.4 1847.29   472.8 1848.55   485.5 1850.83   494.6 1850.71   498.8 1852.32
   507.1 1859.86   521.1 1870.76   536.2 1877.69   561.1 1894.01     573 1900.42
   582.8 1903.33   606.8 1913.54   648.3  1926.8   669.1 1930.84   699.9 1934.35
#Mann= 5 ,-1,0
       0     .03       0     110      .1       0     190    .025       0
  260.65    .045       0  453.27      .1       0
Bank Sta=260.65,453.27
XS Rating Curve= 0 ,0
Exp/Cntr=0.3,0.1

Type RM Length L Ch R = 1 ,24216   ,496.2,502.7,511.6
XS GIS Cut Line= 4
     2263643.189      709712.8192263556.71022462709944.577937843
2263448.35644746710286.6221068472263390.96741648 710538.79829322
#Sta/Elev= 30
       0 1945.46    21.7  1945.4    38.8 1940.97    55.9 1931.14    68.7 1916.31
   100.2 1906.54   128.5 1893.12     137  1892.1   154.1 1882.11   167.4  1879.1
   188.2 1869.12   201.6 1866.38   256.4 1845.96     290 1846.29  312.81 1834.52
   319.3 1832.56   558.5 1832.59  566.271834.521   579.5 1838.57   593.5 1846.81
   621.1 1847.45   641.6 1853.37   661.1 1854.94   674.4 1864.06   690.8 1866.63
   703.1 1877.41   802.3 1913.54   842.4 1934.15   854.9 1933.22   864.8 1937.47
#Mann= 4 ,-1,0
       0      .1       0  312.81    .045       0  566.27    .025       0
  567.37      .1       0
Bank Sta=312.81,566.27
XS Rating Curve= 0 ,0
Exp/Cntr=0.3,0.1

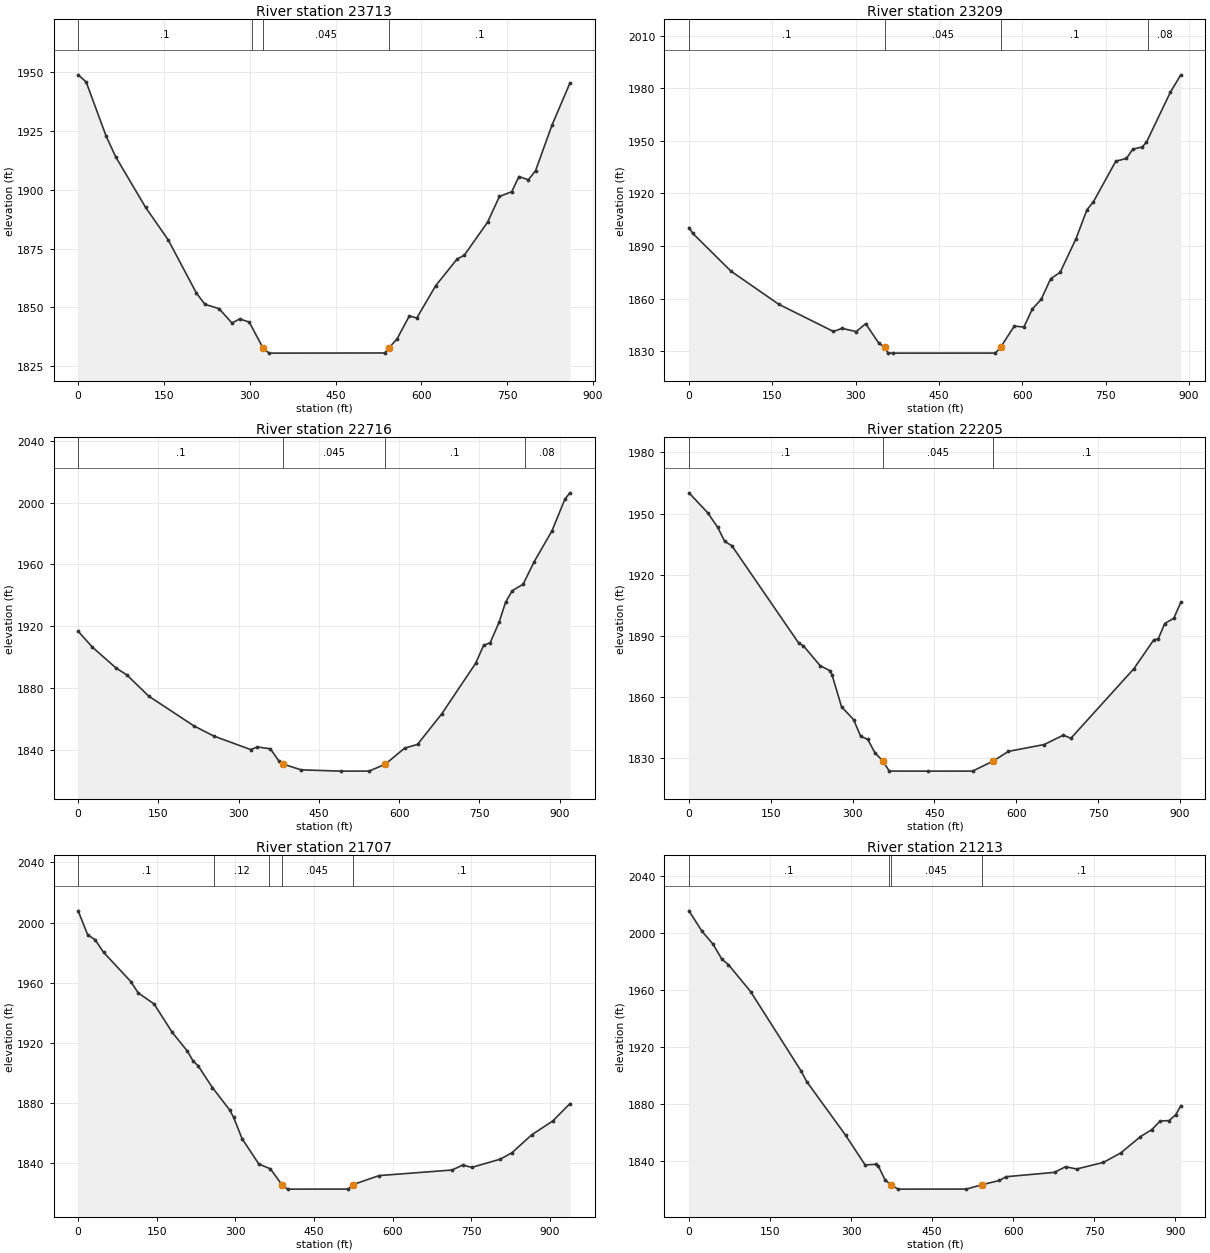
Type RM Length L Ch R = 1 ,23713   ,452.4,504.3,562
XS GIS Cut Line= 5
2263232.25741881709609.8501282212263082.70329821709815.789305293
     2263021.788      709970.1162262958.27725046710128.120249255
2262886.42713493710387.243715537
#Sta/Elev= 30
       0 1948.82      14 1945.81    48.6 1923.01    65.4  1914.1   117.8 1892.57
   157.4 1878.73   206.8 1856.09   221.6 1851.36   246.3  1849.5   268.9 1843.42
   282.2 1845.13     299 1843.82  322.87 1832.93   333.4 1830.62   535.8 1830.69
  543.481832.931   557.4 1836.67   578.9 1846.45   591.8 1845.52     625 1859.29
   662.4  1870.6   674.8 1872.17   715.6 1886.24   736.3 1897.16   757.9 1899.18
   770.3 1905.62   786.9 1904.24   799.4 1908.07   828.4 1927.59   859.6 1945.35
#Mann= 4 ,-1,0
       0      .1       0  304.51    .025       0  322.87    .045       0
  543.48      .1       0
Bank Sta=322.87,543.48
XS Rating Curve= 0 ,0
Exp/Cntr=0.3,0.1

Type RM Length L Ch R = 1 ,23209   ,449.8,492.4,539.8
XS GIS Cut Line= 4
2262974.32078855709490.5273656632262780.28830053709567.608796805
 2262461.0490886709822.1093590552262253.67104206709992.389253505
#Sta/Elev= 30
       0 1900.51     6.6 1897.25    75.5 1875.64   161.6 1856.72   260.1  1841.2
   275.5    1843     301 1841.12   318.1 1845.64   341.9 1834.43  352.711832.149
     358 1828.97   366.5 1828.85   551.5 1828.88  560.871832.152   585.7 1844.32
   602.8 1843.69   618.2 1854.08   634.1 1859.55   651.1  1871.3   668.2 1874.97
   696.6 1894.03   716.4 1910.65   727.9 1915.09   768.3 1938.35   787.5 1939.92
   798.9 1945.21     816 1946.49   823.6 1949.24   866.6 1977.73   885.4 1987.63
#Mann= 4 ,-1,0
       0      .1       0  352.71    .045       0  560.87      .1       0
  827.05     .08       0
Bank Sta=352.71,560.87
XS Rating Curve= 0 ,0
Exp/Cntr=0.3,0.1

Type RM Length L Ch R = 1 ,22716   ,531.4,511.8,492.4
XS GIS Cut Line= 4
2262870.00342524709177.2973546242262564.65434011709229.650633319
     2262413.458709262.486216771     2261971.085709368.932216771
#Sta/Elev= 30
       0 1916.83    26.2 1906.69    70.8 1893.05    91.1 1888.57   131.7 1874.92
   216.9  1855.5   253.5 1849.06   322.6 1840.27   334.9 1841.98   359.4 1840.77
   375.8 1832.67  383.691830.847   416.7 1827.18   490.5 1826.34   544.1 1826.38
  574.241830.847   610.4  1841.2   634.5 1843.63   680.1 1863.53   743.1 1896.04
     758 1907.64   770.3  1909.4   786.8 1922.48   799.1 1935.57   811.4 1942.95
     832 1947.28   852.7 1961.89   885.7 1981.63   910.2 2002.38   919.5 2006.34
#Mann= 4 ,-1,0
       0      .1       0  383.69    .045       0  574.24      .1       0
  834.53     .08       0
Bank Sta=383.69,574.24
XS Rating Curve= 0 ,0
Exp/Cntr=0.3,0.1

Type RM Length L Ch R = 1 ,22205   ,536.2,498.1,459.3
XS GIS Cut Line= 4
2262724.03728534708579.6551413562262440.33782712708705.251301101
2262094.79280942708857.5160572742261913.11856542708970.769992119
#Sta/Elev= 30
       0 1960.16    34.4 1950.36    52.6 1943.25    65.5 1936.29    78.6  1934.2
   201.1  1886.4   209.8 1885.05   240.4 1875.32   258.8 1872.76   262.3 1870.79
   279.8 1855.07   301.7 1848.85   314.8 1840.66   327.9 1839.05     341 1832.49
  355.481828.456   367.3 1823.53     439  1823.5   520.2 1823.52  557.861828.456
   585.8  1833.2   651.4 1836.56   686.4 1841.15   700.4 1839.65   815.8 1873.79
   852.1 1887.89   860.8 1888.61   872.4 1895.99   888.9 1898.53   901.9  1906.4
#Mann= 3 ,-1,0
       0      .1       0  355.48    .045       0  557.86      .1       0
Bank Sta=355.48,557.86
XS Rating Curve= 0 ,0
Exp/Cntr=0.3,0.1

Type RM Length L Ch R = 1 ,21707   ,528.4,493.5,456.1
XS GIS Cut Line= 4
     2262324.425       708015.682262089.36860515708279.792352793
2261845.82572664708578.4599702762261754.63728154708755.748577109
#Sta/Elev= 30
       0 2007.78    18.2 1991.85    32.4 1988.58    48.5 1980.21   100.4 1960.77
   114.7 1953.15   144.8 1945.88   179.7 1926.86   208.1 1914.63   219.4 1907.86
     229 1904.69   256.2 1890.22   289.2 1875.28   296.5 1870.51   312.6 1856.36
   344.7 1839.41   366.8 1836.16  388.611825.697   399.8 1822.69   515.4 1822.72
  524.251825.695   574.3  1831.7   713.6 1835.41   733.5  1838.7   751.1 1837.16
     805 1842.58   827.5 1846.86     865 1858.72   905.6 1868.05   938.3 1879.57
#Mann= 5 ,-1,0
       0      .1       0     260     .12       0  363.56    .025       0
  388.61    .045       0  524.25      .1       0
Bank Sta=388.61,524.25
XS Rating Curve= 0 ,0
Exp/Cntr=0.3,0.1

Type RM Length L Ch R = 1 ,21213   ,521.5,500,477.6
XS GIS Cut Line= 3
     2261660.031      707729.413     2261572.331      708175.881
     2261485.345       708622.49
#Sta/Elev= 30
       0 2015.39    24.2 2000.97      44 1992.26    60.9 1981.44    73.1 1977.57
   113.9 1958.77   207.7 1902.83   217.7  1895.6   289.8 1857.88   325.9 1837.05
   346.3 1837.52   350.3  1836.3   362.6 1826.73  373.091823.134     387 1820.07
   513.4 1820.11  541.931823.134   574.5 1826.18   586.7 1828.78   676.4 1831.85
   696.8 1835.83   717.1 1834.19   766.6 1838.81   798.6 1845.41   835.3 1856.89
   856.3 1861.88     872  1867.9   888.3 1868.16   900.5 1872.28     910 1878.58
#Mann= 4 ,-1,0
       0      .1       0     370    .025       0  373.09    .045       0
  541.93      .1       0
Bank Sta=373.09,541.93
XS Rating Curve= 0 ,0
Exp/Cntr=0.3,0.1

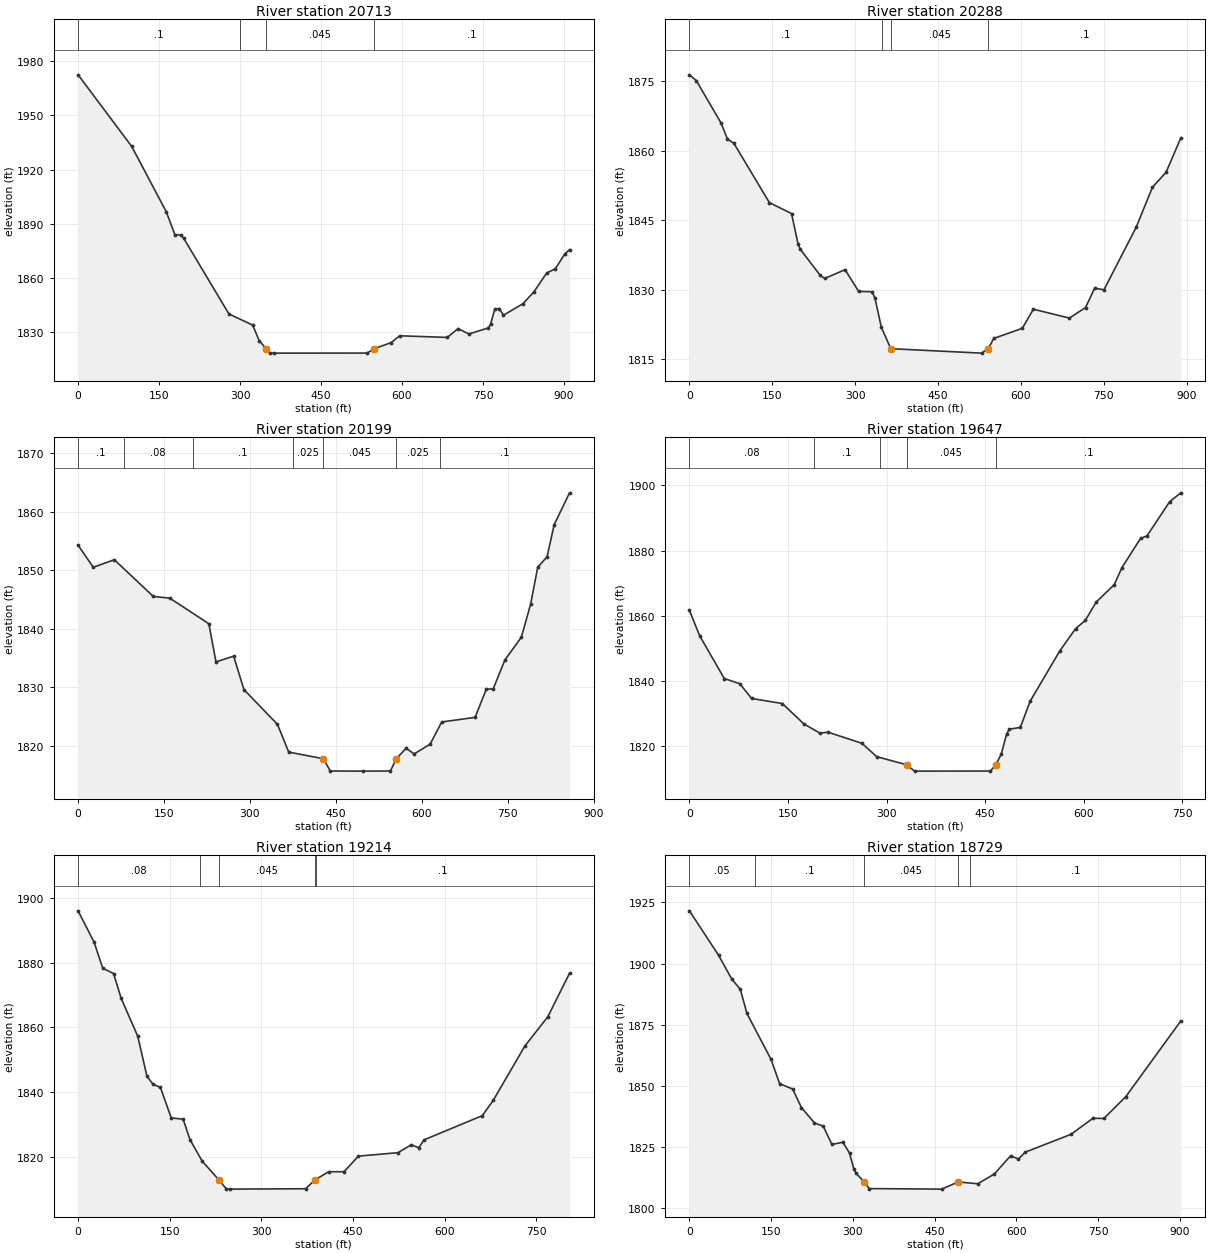
Type RM Length L Ch R = 1 ,20713   ,488.9,424.8,387.4
XS GIS Cut Line= 3
     2261058.355      707689.975     2261074.573      708144.362
     2261099.448      708599.334
#Sta/Elev= 30
       0 1972.31    99.3 1932.75   163.3 1896.69   179.3 1883.97   190.4 1883.87
   195.3 1882.16   279.4 1840.22   323.4 1834.08   335.4 1825.48  348.431821.006
   355.4 1818.62   363.4 1818.59   535.6 1818.62  548.431821.007   579.7 1824.38
   595.7 1828.17   683.8 1827.27   703.9 1832.16   723.9 1829.15   759.9 1832.52
     764 1834.52     772 1842.98     780 1843.19     788 1839.54     824 1845.88
   844.1 1852.34   868.1 1862.88   884.1 1865.19   901.4 1873.29   910.3 1875.72
#Mann= 4 ,-1,0
       0      .1       0     300    .025       0  348.43    .045       0
  548.43      .1       0
Bank Sta=348.43,548.43
XS Rating Curve= 0 ,0
Exp/Cntr=0.3,0.1

Type RM Length L Ch R = 1 ,20288   ,109.3,89.6,82.8
XS GIS Cut Line= 4
2260560.85999736707784.7837047212260542.38266186 708061.94373715
2260758.67617736 708365.189419692260826.62052544708594.684794849
#Sta/Elev= 30
       0 1876.33    12.4 1875.09    57.4 1865.91    68.7 1862.52    80.6 1861.54
   144.7 1848.78   184.8 1846.42   196.8 1839.77   200.8  1838.7   236.9 1833.07
   244.9 1832.43   281.7 1834.32   306.3 1829.64   330.9 1829.56     336 1828.14
   347.3 1821.93   364.5 1817.29   528.8 1816.33     541 1817.31   550.9  1819.5
   602.6 1821.68   622.6  1825.8   687.8 1823.89     717 1826.15   733.7 1830.35
   750.4 1829.98   808.8 1843.47   838.1 1852.08     863 1855.35   889.6 1862.75
#Mann= 4 ,-1,0
       0      .1       0  347.78    .025       0   364.5    .045       0
     541      .1       0
Bank Sta=364.5,541
XS Rating Curve= 0 ,0
Exp/Cntr(USF)=0,0
Exp/Cntr=0.3,0.1

Type RM Length L Ch R = 1 ,20199   ,518.4,551.7,580.6
XS GIS Cut Line= 4
2260231.91622592707937.7637437942260449.63589411708121.924129172
2260678.59389181708381.9418521362260724.87699267708603.572901803
#Sta/Elev= 30
       0 1854.26    26.5  1850.5    63.2 1851.79   131.3 1845.52   160.1 1845.23
   228.3 1840.86   240.7 1834.34   271.6 1835.33   289.5 1829.63   348.1 1823.68
   367.7 1818.95   428.2 1817.82   440.3 1815.72   497.4  1815.7   545.3 1815.73
   555.7 1817.83   572.7  1819.6   586.8 1818.64   614.6  1820.3   634.9 1824.09
   693.2 1824.88   712.6 1829.67   724.8 1829.76   745.3  1834.7   773.9 1838.55
   790.2 1844.24   802.5 1850.51   818.8 1852.29   831.1 1857.73     858 1863.21
#Mann= 7 ,-1,0
       0      .1       0      80     .08       0     200      .1       0
  375.16    .025       0   428.2    .045       0   555.7    .025       0
  631.62      .1       0
Bank Sta=428.2,555.7
XS Rating Curve= 0 ,0
Exp/Cntr=0.3,0.1

Type RM Length L Ch R = 1 ,19647   ,486.1,433,396.1
XS GIS Cut Line= 4
2259992.41032475708102.1866191682260044.44881158708284.636973315
2260119.25597048708587.8399217632260263.77949299708786.904747644
#Sta/Elev= 30
       0 1861.66    15.6 1853.85      53 1840.74    76.7 1839.14    94.6 1834.62
   141.4 1833.06   174.1 1826.82   198.5 1823.98   210.9 1824.27   262.6 1820.84
     285 1816.76   330.4 1814.27   342.7 1812.31   458.1 1812.34   466.3 1814.22
   474.6 1817.54   482.8 1823.69   486.9 1825.19   503.7 1825.73   518.5 1833.74
   563.8 1849.23   587.7 1856.03   602.5 1858.57   619.3 1864.24   646.6 1869.55
   658.3 1874.78   686.6 1883.74   696.5 1884.54   731.1 1895.06     748 1897.75
#Mann= 5 ,-1,0
       0     .08       0  189.73      .1       0  289.73    .025       0
   330.4    .045       0   466.3      .1       0
Bank Sta=330.4,466.3
XS Rating Curve= 0 ,0
Exp/Cntr=0.3,0.1

Type RM Length L Ch R = 1 ,19214   ,564.5,484.8,428.1
XS GIS Cut Line= 4
2259441.54842232 708431.29182712 2259578.2158328708532.224928297
2259858.66075741708786.8015870552260088.16272721708899.916020432
#Sta/Elev= 30
       0 1895.93    26.1 1886.29    40.4 1878.23      58 1876.62    70.5 1868.96
    97.6 1857.31   112.7 1844.98   122.6  1842.5   134.8 1841.52   152.4 1832.15
     172 1831.71   183.2 1825.42   203.1 1818.83  230.631813.003   242.7 1810.26
   248.2 1810.19   372.4 1810.31   387.61813.003   410.2 1815.55   435.3 1815.55
   458.9 1820.36   523.7 1821.42   545.7 1823.89   557.5 1822.92   566.5 1825.38
   661.8 1832.84   679.7 1837.56   731.4 1854.28   768.9 1863.27   804.5 1876.68
#Mann= 5 ,-1,0
       0     .08       0   199.9    .025       0  230.63    .045       0
   387.6    .025       0   389.9      .1       0
Bank Sta=230.63,387.6
XS Rating Curve= 0 ,0
Exp/Cntr=0.3,0.1

Type RM Length L Ch R = 1 ,18729   ,522.2,516.7,513.3
XS GIS Cut Line= 4
2259186.74662888709101.2812896692259441.79517068709107.407476011
2259826.05986443709061.3411240132260084.96957751 709082.97509301
#Sta/Elev= 30
       0 1921.52    53.4 1903.39    77.5 1893.74    93.5 1889.41   105.5 1879.62
   149.8 1860.86   165.5 1850.94   189.5 1848.76   205.5 1841.18   229.5 1834.91
   245.5 1833.61   261.5 1826.15   281.7 1827.02   293.8 1822.64   301.8 1816.08
   305.6 1814.42   320.4 1810.93     330 1808.11     463 1807.89   493.3 1810.83
   529.1 1810.08   559.7 1814.06   589.4 1821.48     604 1820.18   616.1 1822.95
   700.5 1830.29   740.6 1836.82   760.7 1836.75   800.8  1845.6     902 1876.59
#Mann= 5 ,-1,0
       0     .05       0     120      .1       0   320.4    .045       0
   493.3    .025       0  515.12      .1       0
Bank Sta=320.4,493.3
XS Rating Curve= 0 ,0
Exp/Cntr=0.3,0.1

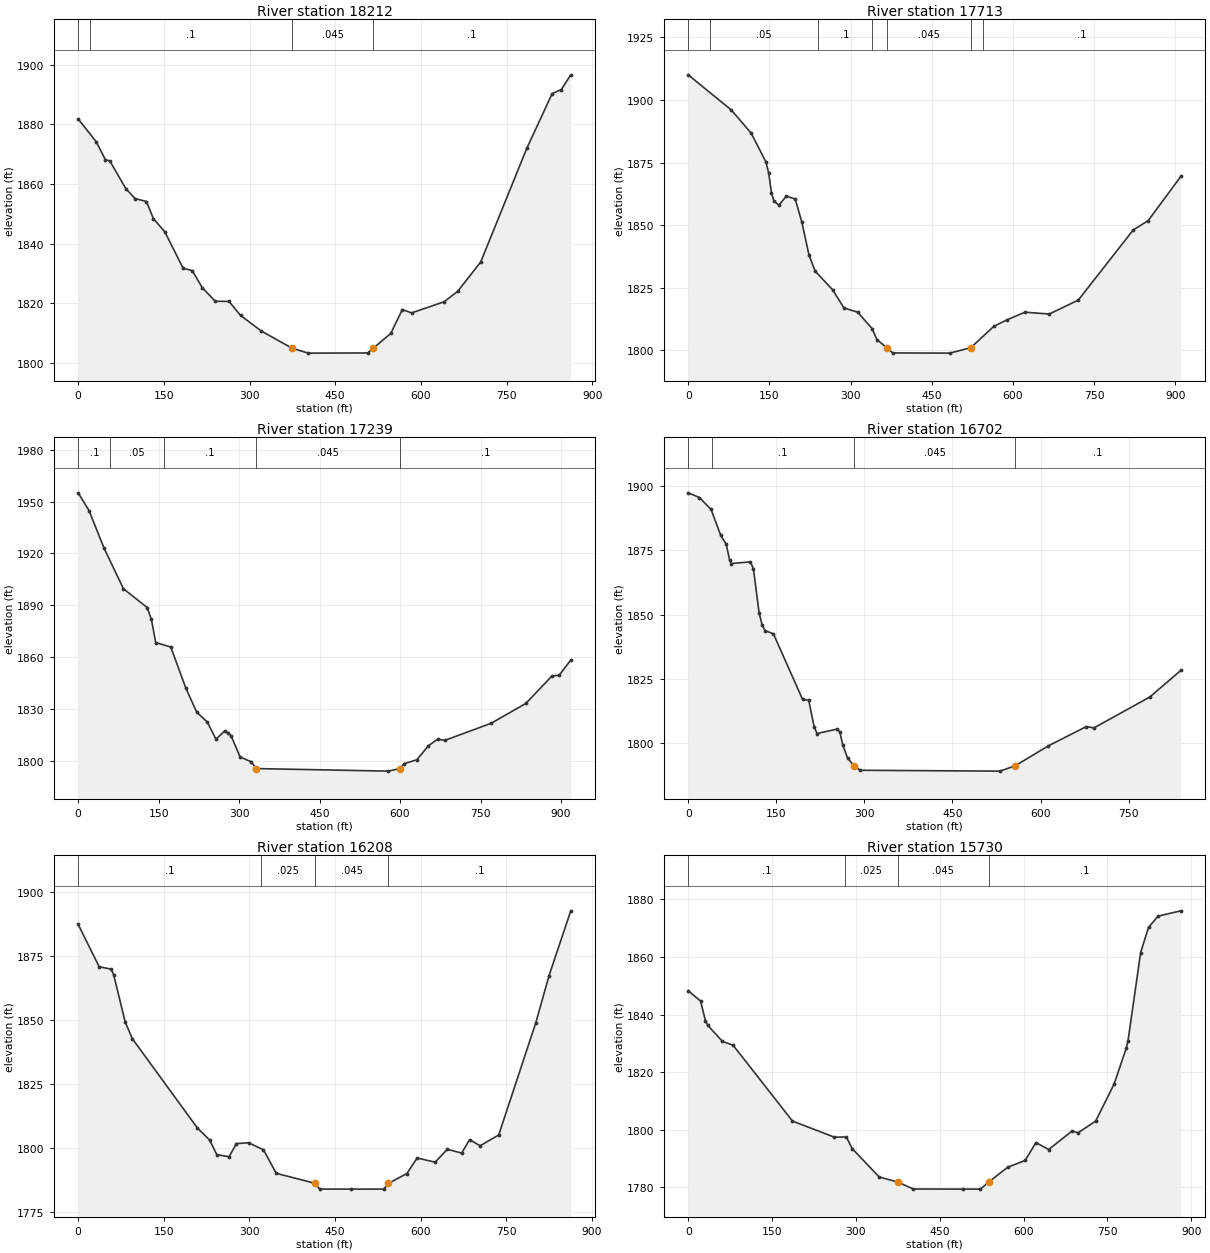
Type RM Length L Ch R = 1 ,18212   ,503.8,499.5,496.1
XS GIS Cut Line= 4
     2259288.719      709628.9462259514.69730365 709618.35954142
2259869.47669878709564.6808090042260144.57001168709529.213859228
#Sta/Elev= 30
       0 1881.84    31.5 1874.22    47.5 1868.22    55.5 1867.73    83.5 1858.43
    99.6 1855.13   119.6 1854.12   131.6 1848.41   151.6 1843.99   183.7 1831.71
   199.7 1830.92   217.3 1825.17   239.9 1820.63   264.1 1820.56   284.4 1815.84
   320.8 1810.61   374.3 1804.86   402.9  1803.2   506.9 1803.26   516.7 1804.87
   547.3 1809.83   567.5 1817.84   583.7  1816.7   640.6 1820.45   664.4 1823.94
   704.7  1833.8   785.4 1871.98   829.8 1890.36   845.9 1891.72   862.4 1896.67
#Mann= 4 ,-1,0
       0     .05       0      20      .1       0   374.3    .045       0
   516.7      .1       0
Bank Sta=374.3,516.7
XS Rating Curve= 0 ,0
Exp/Cntr=0.3,0.1

Type RM Length L Ch R = 1 ,17713   ,473.6,474.2,492
XS GIS Cut Line= 3
     2259366.285      710168.486     2259812.265      710078.336
     2260258.245      709988.187
#Sta/Elev= 30
       0    1910    79.5    1896   116.2 1886.77   143.6 1875.25   148.8 1870.68
   153.8 1862.94     158 1859.78   167.4 1857.95   181.5  1861.6   197.8  1860.4
   210.1 1851.09   223.2 1838.04   234.5 1831.65   267.2  1824.1   287.6 1816.96
   313.3 1815.23   339.7 1808.71   348.8 1804.28  366.861801.065   377.8 1798.99
   483.1 1798.91  521.921801.066   564.5 1809.58   588.3 1812.14   622.2 1815.25
   667.1 1814.52   720.7 1820.09   822.2 1848.09   849.7 1851.79     910 1869.42
#Mann= 7 ,-1,0
       0      .1       0      40     .05       0     240      .1       0
     340    .025       0  366.86    .045       0  521.92    .025       0
     545      .1       0
Bank Sta=366.86,521.92
XS Rating Curve= 0 ,0
Exp/Cntr=0.3,0.1

Type RM Length L Ch R = 1 ,17239   ,459.4,536.7,627.7
XS GIS Cut Line= 4
2259544.05227863710579.0268650662259813.44519614710558.221169775
2260175.30111978710470.158171842     2260423.619710350.696158285
#Sta/Elev= 30
       0 1955.03    20.2 1944.79    48.3 1922.95    84.4 1899.53   128.5 1888.65
   136.5 1881.73   144.6 1868.37   172.6 1865.78   200.7 1842.02   220.8 1828.15
   240.8 1822.34   256.9 1812.43     273 1817.21   279.9 1816.14   285.4 1814.14
   301.8 1802.16   322.4  1799.4  331.851795.446   577.6 1793.96  600.471795.445
   607.7 1798.29   631.2 1800.51     653 1808.67   670.2 1812.45   683.5 1811.77
   769.9 1821.67   834.5 1833.15   883.3  1849.1   896.6 1849.43   918.2 1858.26
#Mann= 5 ,-1,0
       0      .1       0      60     .05       0     160      .1       0
  331.85    .045       0  600.47      .1       0
Bank Sta=331.85,600.47
XS Rating Curve= 0 ,0
Exp/Cntr=0.3,0.1

Type RM Length L Ch R = 1 ,16702   ,430.5,493.7,568.7
XS GIS Cut Line= 3
2259514.13441185 710820.743268392259720.81910485  710969.5950832
2260260.98200946711191.682995271
#Sta/Elev= 30
       0 1897.36      19 1895.54      39 1890.89    55.5 1880.77    64.8 1877.34
    70.5 1871.25    73.4 1869.84     106  1870.5     111 1867.83   120.8 1850.61
   125.7 1846.12   130.7 1843.76   145.1 1842.53   194.8 1816.96   205.2 1816.69
   214.5 1806.25   219.4 1803.72     254 1805.45   258.3 1804.21   263.1 1799.36
   271.3  1794.2  282.061791.165   292.9 1789.41   530.8 1789.08  556.841791.166
     613 1798.89   677.8  1806.4   690.8 1805.89     786 1817.93   838.7 1828.26
#Mann= 4 ,-1,0
       0     .05       0      40      .1       0  282.06    .045       0
  556.84      .1       0
Bank Sta=282.06,556.84
XS Rating Curve= 0 ,0
Exp/Cntr=0.3,0.1

Type RM Length L Ch R = 1 ,16208   ,477.3,478,479.7
XS GIS Cut Line= 4
2259383.74190699710946.9398352592259500.47362718711245.487602977
2259636.24255623711512.2413392072259759.24314438 711722.15044377
#Sta/Elev= 30
       0 1887.33    36.8 1870.78    58.2 1869.82    62.5  1867.4    82.3 1849.28
    94.7 1842.74   208.9 1807.82   230.5 1803.07   242.9 1797.41   264.4 1796.57
   277.3 1801.71   298.5 1802.04   324.7  1799.3   347.1  1790.1   414.5 1786.23
   423.4 1783.96   477.3 1783.93   535.6 1783.94  543.741786.189     576 1790.02
     594 1796.09   625.6 1794.45   646.8  1799.5     672 1798.01   685.9 1803.25
   704.4 1800.87   736.9 1805.07   801.9 1848.88   825.1  1867.3   863.2 1892.61
#Mann= 4 ,-1,0
       0      .1       0     320    .025       0   414.5    .045       0
  543.74      .1       0
Bank Sta=414.5,543.74
XS Rating Curve= 0 ,0
Exp/Cntr=0.3,0.1

Type RM Length L Ch R = 1 ,15730   ,584.7,512.7,456.9
XS GIS Cut Line= 4
2258955.26441067711176.7627207032259068.01545082711442.431435604
2259206.23140831 711727.660253292259416.03498345711906.643875719
#Sta/Elev= 30
       0 1848.27    22.2 1844.67    30.9 1837.83    35.2 1836.21    61.3 1830.67
    80.3 1829.36   186.6 1803.03   261.2 1797.46   282.9 1797.49   293.8 1793.39
   341.7 1783.63  374.731781.878   402.8 1779.45   490.8 1779.41   522.8 1779.42
  537.671781.878   571.7 1787.02   602.8 1789.35   622.2 1795.57   644.9 1793.16
     687 1799.61   697.5 1798.95     729 1803.02     762 1815.87   783.9 1828.43
   786.8 1830.75   809.5 1861.52   823.6 1870.24   840.7 1874.15   881.3 1875.99
#Mann= 4 ,-1,0
       0      .1       0     280    .025       0  374.73    .045       0
  537.67      .1       0
Bank Sta=374.73,537.67
XS Rating Curve= 0 ,0
Exp/Cntr=0.3,0.1

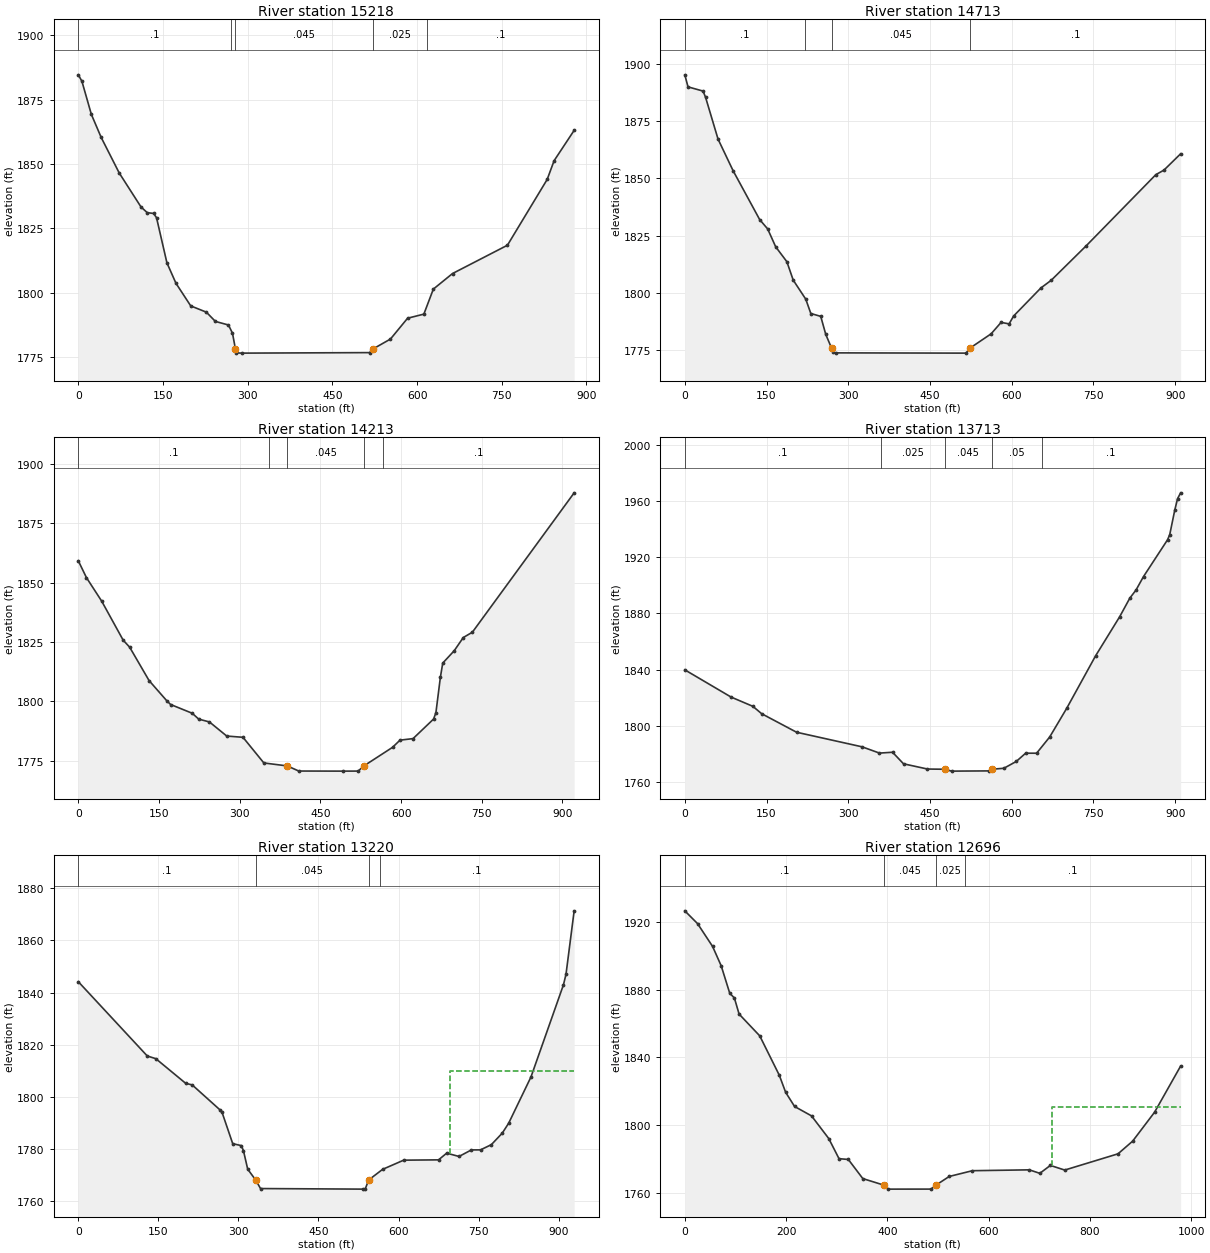
Type RM Length L Ch R = 1 ,15218   ,419.4,504.8,549.3
XS GIS Cut Line= 4
2258411.57625378711653.2998851972258586.13603783711818.587880448
2258886.15288496711993.0970085092259125.38271299712158.215688816
#Sta/Elev= 30
       0 1884.68     6.3  1882.2    23.1  1869.3    40.5 1860.35    72.4 1846.56
     111 1833.36     122 1831.15   133.3 1830.83   138.5 1829.19   156.9 1811.66
   172.9 1803.72   199.1 1794.92   226.7  1792.5   242.8 1788.89   265.9 1787.51
     273 1784.34  278.271778.195   279.8 1776.68     289 1776.58   515.8 1776.78
  521.841778.196   552.8 1782.04   583.2 1790.14     612 1791.73   628.8 1801.45
   662.8  1807.5     760 1818.49   830.4 1844.04   842.7 1851.33   878.2 1863.12
#Mann= 5 ,-1,0
       0      .1       0   270.4    .025       0  278.27    .045       0
  521.84    .025       0  617.48      .1       0
Bank Sta=278.27,521.84
XS Rating Curve= 0 ,0
Exp/Cntr=0.3,0.1

Type RM Length L Ch R = 1 ,14713   ,486.3,500,511.4
XS GIS Cut Line= 3
     2258141.987      711836.069     2258366.294      712231.937
     2258590.601      712627.805
#Sta/Elev= 30
       0 1895.08     5.9 1889.83    33.5 1887.99    38.1  1885.3      61 1867.06
    88.6 1853.29   137.4 1831.96   152.1 1827.88   166.8 1820.09   187.3  1813.6
     199 1805.55     222 1797.26   231.3    1791   249.5 1789.75   258.7  1781.9
  269.361775.905   272.5 1774.05   277.1 1773.83   516.2 1773.72  523.421775.907
   562.2 1782.14   580.5 1787.12   595.2 1786.48   603.5 1789.91   653.5 1802.13
   672.5 1805.49   736.9 1820.57   864.5 1851.55   879.4 1853.53     910 1860.64
#Mann= 4 ,-1,0
       0      .1       0     220    .025       0  269.36    .045       0
  523.42      .1       0
Bank Sta=269.36,523.42
XS Rating Curve= 0 ,0
Exp/Cntr=0.3,0.1

Type RM Length L Ch R = 1 ,14213   ,477.8,500.2,525
XS GIS Cut Line= 4
2257831.06955433711970.0505776832257854.72497426712283.590029139
     2257906.819      712426.786     2258060.062      712855.197
#Sta/Elev= 30
       0 1859.21    15.1 1852.14    43.3 1842.29    83.4  1825.8    95.4 1822.87
   131.5 1808.81   164.3 1800.34   171.6 1798.73   211.7 1795.05   223.8 1792.58
   243.8 1791.38   275.9 1785.45   306.1 1784.92   344.9 1774.12   388.5 1772.87
   409.8 1770.72   491.6 1770.68   520.3  1770.7  530.431772.806   584.1 1780.69
     598 1783.72   622.3 1784.37   660.5 1792.62   664.8  1795.3   673.1 1810.21
   677.5 1816.17   698.8 1821.37   715.7 1826.93   732.6 1829.17   921.8 1887.85
#Mann= 5 ,-1,0
       0      .1       0  354.43    .025       0   388.5    .045       0
  530.43     .05       0  566.81      .1       0
Bank Sta=388.5,530.43
XS Rating Curve= 0 ,0
Exp/Cntr=0.3,0.1

Type RM Length L Ch R = 1 ,13713   ,509.7,492.5,490.3
XS GIS Cut Line= 3
2257436.55725351711960.347422891 2257413.4192535712414.759422891
2257390.28125351712869.170422891
#Sta/Elev= 30
       0 1839.82    84.9 1820.42     125  1813.8     141 1808.57   205.1 1795.36
   325.3 1784.97   357.3  1780.5   381.3  1781.1   401.4 1772.87   445.4 1769.14
   477.5 1768.98   489.5 1767.65   557.6 1767.81  563.031768.996   585.6 1769.68
   608.2 1774.51   625.6 1780.43   645.7 1780.41   669.7 1791.97     701 1812.45
   753.8  1849.7   798.1 1877.62   816.7 1890.85   828.2 1896.71   841.9 1906.27
     886 1932.46     890 1936.11   899.3  1953.7   904.4 1961.77     910 1965.91
#Mann= 5 ,-1,0
       0      .1       0     360    .025       0   477.5    .045       0
  563.03     .05       0     655      .1       0
Bank Sta=477.5,563.03
XS Rating Curve= 0 ,0
Exp/Cntr=0.3,0.1

Type RM Length L Ch R = 1 ,13220   ,635.2,524,420.1
XS GIS Cut Line= 3
      2256941.61      711956.1012256917.74574225 712510.01254559
2257112.08924711712830.382299393
#Sta/Elev= 30
       0 1844.14   129.2 1815.62   145.2 1814.59   201.3  1805.1   213.3 1804.53
   265.3 1794.95   269.3 1793.98   289.3 1781.95   305.4  1781.2   309.4 1779.26
   317.4 1772.14  332.27 1768.01   341.4 1764.71   533.6 1764.49   537.6 1764.56
  544.111768.011   570.1 1772.08   609.6 1775.61     675 1775.73   690.2  1778.3
   713.4 1777.04   736.5 1779.55   753.6 1779.56     774 1781.58   794.4    1786
   806.4 1789.81   848.2 1807.58     909 1842.93   913.8 1846.98   929.1 1871.37
#Mann= 4 ,-1,0
       0      .1       0  332.27    .045       0  544.11    .025       0
  564.43      .1       0
#XS Ineff= 2 , 0
                          696.75         1809.88
Permanent Ineff=
       F       F
Bank Sta=332.27,544.11
XS Rating Curve= 0 ,0
Exp/Cntr=0.3,0.1

Type RM Length L Ch R = 1 ,12696   ,398.9,391.3,387.3
XS GIS Cut Line= 4
      2256124.47      712539.8862256428.65606416 712648.13901465
2256878.24989452712777.0279167152257034.96304073712881.644248026
#Sta/Elev= 30
       0 1926.51    25.2 1918.95    54.9 1905.47    71.9 1894.01    88.8 1877.79
    97.9 1875.06   107.2 1865.54     148 1852.66   186.5 1829.48   199.2 1819.29
   216.8 1810.96   250.2 1805.42   284.2 1792.05   304.5 1780.14   322.9 1779.68
   351.5 1768.38   393.1 1764.52   401.4 1762.16   486.3 1762.18   495.7 1764.47
   522.1 1769.64   567.9 1773.04   680.2 1773.55     701 1771.49   721.8 1776.16
   750.2 1773.42   855.4 1783.01   884.3 1790.51   927.6  1807.6     979 1834.83
#Mann= 4 ,-1,0
       0      .1       0   393.1    .045       0   495.7    .025       0
  552.87      .1       0
#XS Ineff= 2 , 0
                          725.63         1810.91
Permanent Ineff=
       F       F
Bank Sta=393.1,495.7
XS Rating Curve= 0 ,0
Exp/Cntr=0.3,0.1