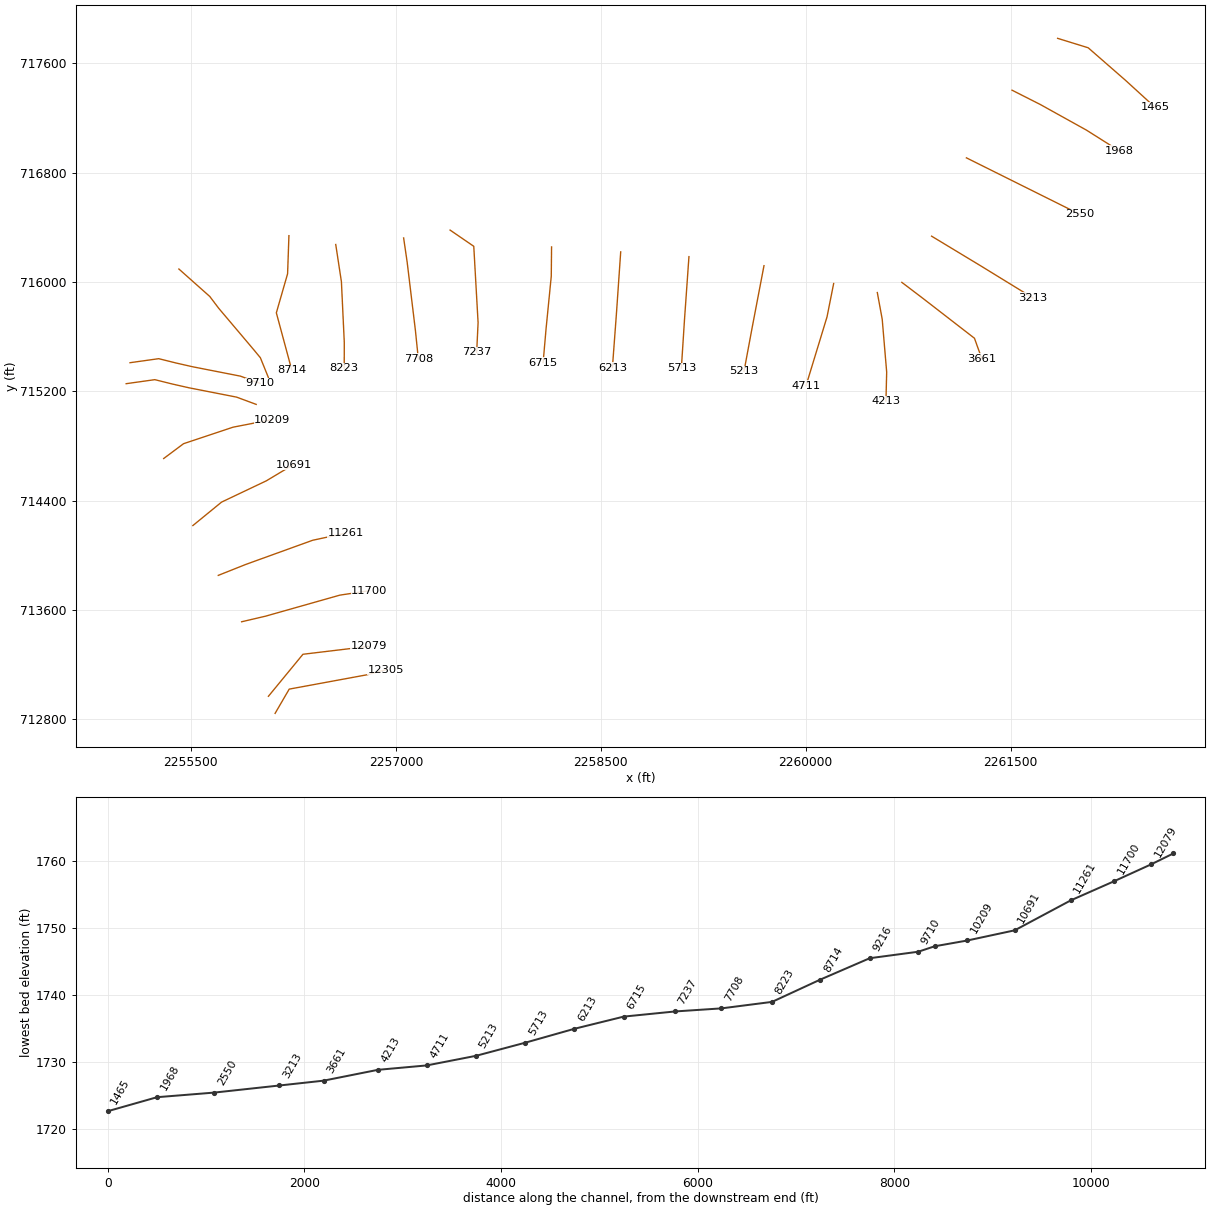
HEC-RAS study TYGVRV1.prj: TYGVRV1

--- TYGVRV1.g01 (geometry) --- (continued)

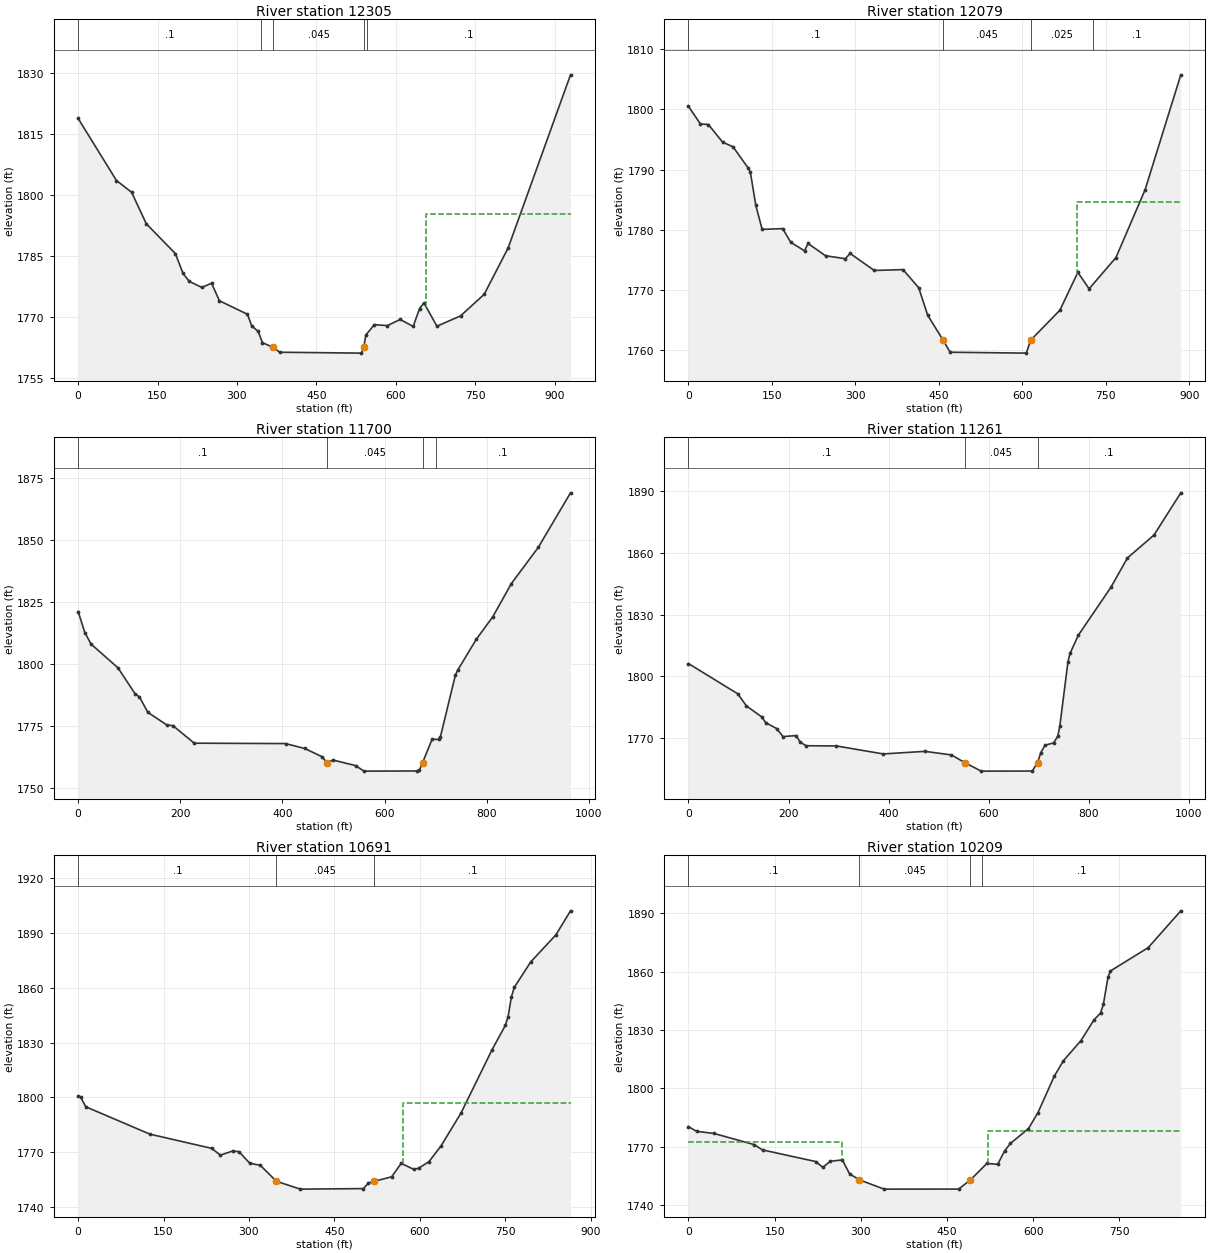
Type RM Length L Ch R = 1 ,12305   ,232.9,225.9,220.8
XS GIS Cut Line= 4
2256116.41543576712841.8962137442256219.68446722713019.410211083
2256791.82916891713124.900828956 2256929.9096445713162.353067116
#Sta/Elev= 30
       0 1818.76    72.4 1803.52     101 1800.64   128.7 1792.91   183.6  1785.6
   198.2  1780.7   209.9 1778.76   233.7 1777.27     252 1778.31   266.9    1774
   319.8 1770.68   327.9 1767.83   340.1 1766.48   348.2 1763.71   368.6 1762.54
   380.8 1761.36   535.3 1761.14  539.681762.614   543.5 1765.58   559.7 1768.14
   584.1 1767.89   608.5 1769.41   632.9 1767.69   645.1 1772.09   653.3 1773.47
   677.8 1767.75   722.4 1770.28   767.2 1775.59   812.4 1786.99   930.2 1829.48
#Mann= 5 ,-1,0
       0      .1       0  345.37    .025       0   368.6    .045       0
  539.68    .025       0  545.37      .1       0
#XS Ineff= 2 , 0
                           657.8         1795.31
Permanent Ineff=
       F       F
Bank Sta=368.6,539.68
XS Rating Curve= 0 ,0
Exp/Cntr=0.3,0.1

Type RM Length L Ch R = 1 ,12079   ,357.7,378.9,388.4
XS GIS Cut Line= 3
2256067.69052505712967.262212102 2256320.2402214713274.518563347
2256803.84709219713332.564966819
#Sta/Elev= 30
       0  1800.5    21.6 1797.57    35.8 1797.48    61.4 1794.55    80.1 1793.78
   107.9 1790.18   111.2  1789.6   121.1 1784.05   132.4 1780.06   169.4 1780.19
   183.7 1777.94   208.6 1776.49   214.9 1777.72   246.4 1775.68   282.1 1775.19
   290.5 1776.07   333.9 1773.24   385.6 1773.38   413.8 1770.37   429.9 1765.81
   458.1 1761.61   470.2 1759.66   607.2 1759.51   614.91761.647   667.6 1766.65
   699.8 1772.93     720 1770.19   768.3 1775.39   820.7 1786.66   884.8 1805.73
#Mann= 4 ,-1,0
       0      .1       0   458.1    .045       0   614.9    .025       0
  727.73      .1       0
#XS Ineff= 2 , 0
                          697.47         1784.62
Permanent Ineff=
       F       F
Bank Sta=458.1,614.9
XS Rating Curve= 0 ,0
Exp/Cntr(USF)=0,0
Exp/Cntr=0.3,0.1

Type RM Length L Ch R = 1 ,11700   ,430.1,439.1,443.1
XS GIS Cut Line= 4
2255871.40152567713512.414845226 2256046.7410972713553.410452965
2256590.29141779713707.2994208772256806.72129605713739.861344408
#Sta/Elev= 30
       0 1821.22    13.1  1812.7    25.4  1808.1    77.9 1798.56   111.7 1788.04
   119.9 1786.88   136.4 1780.64   173.3 1775.59   185.7 1775.25   227.3 1768.22
     406 1768.06   443.5 1766.09   476.7 1762.83  487.541760.378   498.6 1761.45
   543.2 1759.19   559.4 1756.97   663.8 1757.03     668 1757.36  674.191760.381
   692.9 1769.84   705.4 1769.72   709.2 1770.85   738.3 1795.52   742.8 1797.56
   779.2 1809.99   811.6 1819.09     848 1832.47   900.6 1847.01   963.8 1869.01
#Mann= 4 ,-1,0
       0      .1       0  487.54    .045       0  674.19    .025       0
  700.07      .1       0
Bank Sta=487.54,674.19
XS Rating Curve= 0 ,0
Exp/Cntr=0.3,0.1

Type RM Length L Ch R = 1 ,11261   ,568.1,570.5,571.7
XS GIS Cut Line= 4
2255700.53775932713852.0178560172255900.24522805713931.515756692
2256391.61907868 714109.043263272256632.59805166714160.618011134
#Sta/Elev= 30
       0 1806.24    98.6 1791.57   115.9  1785.7     146 1780.47   154.6 1777.59
   176.2 1774.76     189 1770.84   214.9 1771.35   223.4 1768.18   234.9 1766.43
   295.7 1766.32   389.2 1762.45   472.4  1763.7   525.5 1761.97  552.031758.265
   584.9 1754.12     687 1754.16  697.641758.263     704 1763.02   712.5 1766.68
   729.5  1767.8     738 1770.99   742.1 1775.99   758.4 1807.22   762.5 1811.13
   778.9 1819.92   844.3 1843.24   877.1 1857.39   930.2 1868.49   983.8 1888.96
#Mann= 3 ,-1,0
       0      .1       0  552.03    .045       0  697.64      .1       0
Bank Sta=552.03,697.64
XS Rating Curve= 0 ,0
Exp/Cntr=0.3,0.1

Type RM Length L Ch R = 1 ,10691   ,494.8,481.3,471.1
XS GIS Cut Line= 4
2255514.61908488714216.688036875 2255724.7370394714388.353013135
2256052.31586407714544.0729523122256250.33543173 714662.55922143
#Sta/Elev= 30
       0 1800.69     4.3 1800.11    13.4 1794.77     126 1779.77   234.4 1771.99
   249.9 1768.26   271.3 1770.54   282.6 1770.13   301.5  1763.8   319.8 1762.74
  348.161753.944   390.3 1749.64     501 1749.93   509.9 1753.01  520.391753.945
   550.7 1756.41   567.4 1763.75   589.7 1760.45   598.4 1761.17   616.2  1764.7
   637.7 1773.48   672.7 1791.49   727.1 1826.11   750.4 1839.42   755.1 1844.02
   760.8 1854.77     766 1860.22   795.1 1874.23     839 1888.94   864.8 1902.17
#Mann= 3 ,-1,0
       0      .1       0  348.16    .045       0  520.39      .1       0
#XS Ineff= 2 , 0
                           570.4         1796.98
Permanent Ineff=
       F       F
Bank Sta=348.16,520.39
XS Rating Curve= 0 ,0
Exp/Cntr=0.3,0.1

Type RM Length L Ch R = 1 ,10209   ,384.7,334,286.3
XS GIS Cut Line= 4
2255300.89434684714707.2599299012255446.34876562714815.854873355
2255808.09499936714936.5203143772256096.54714319714992.699007093
#Sta/Elev= 30
       0 1780.28    14.1 1777.85      44 1776.78   113.9 1771.06   128.9 1768.29
   221.4 1762.31     234 1759.29   246.7 1762.45   267.8 1763.14   280.4 1755.97
  297.38  1752.9   340.5 1748.12   470.2 1748.14  490.761752.901   519.2 1761.32
   538.1 1760.88   550.3 1767.86   560.3 1771.65   591.5 1779.19   608.2 1787.49
   636.3 1806.06   652.2 1814.08   682.9 1824.51   705.6 1835.16     717 1838.68
   721.9  1843.1     730 1857.07   734.1 1860.31     800 1872.33   856.7 1891.27
#Mann= 4 ,-1,0
       0      .1       0  297.38    .045       0  490.76    .025       0
  511.52      .1       0
#XS Ineff= 2 , 0
          268.01 1772.25  522.02         1777.87
Permanent Ineff=
       F       F
Bank Sta=297.38,490.76
XS Rating Curve= 0 ,0
Exp/Cntr=0.3,0.1

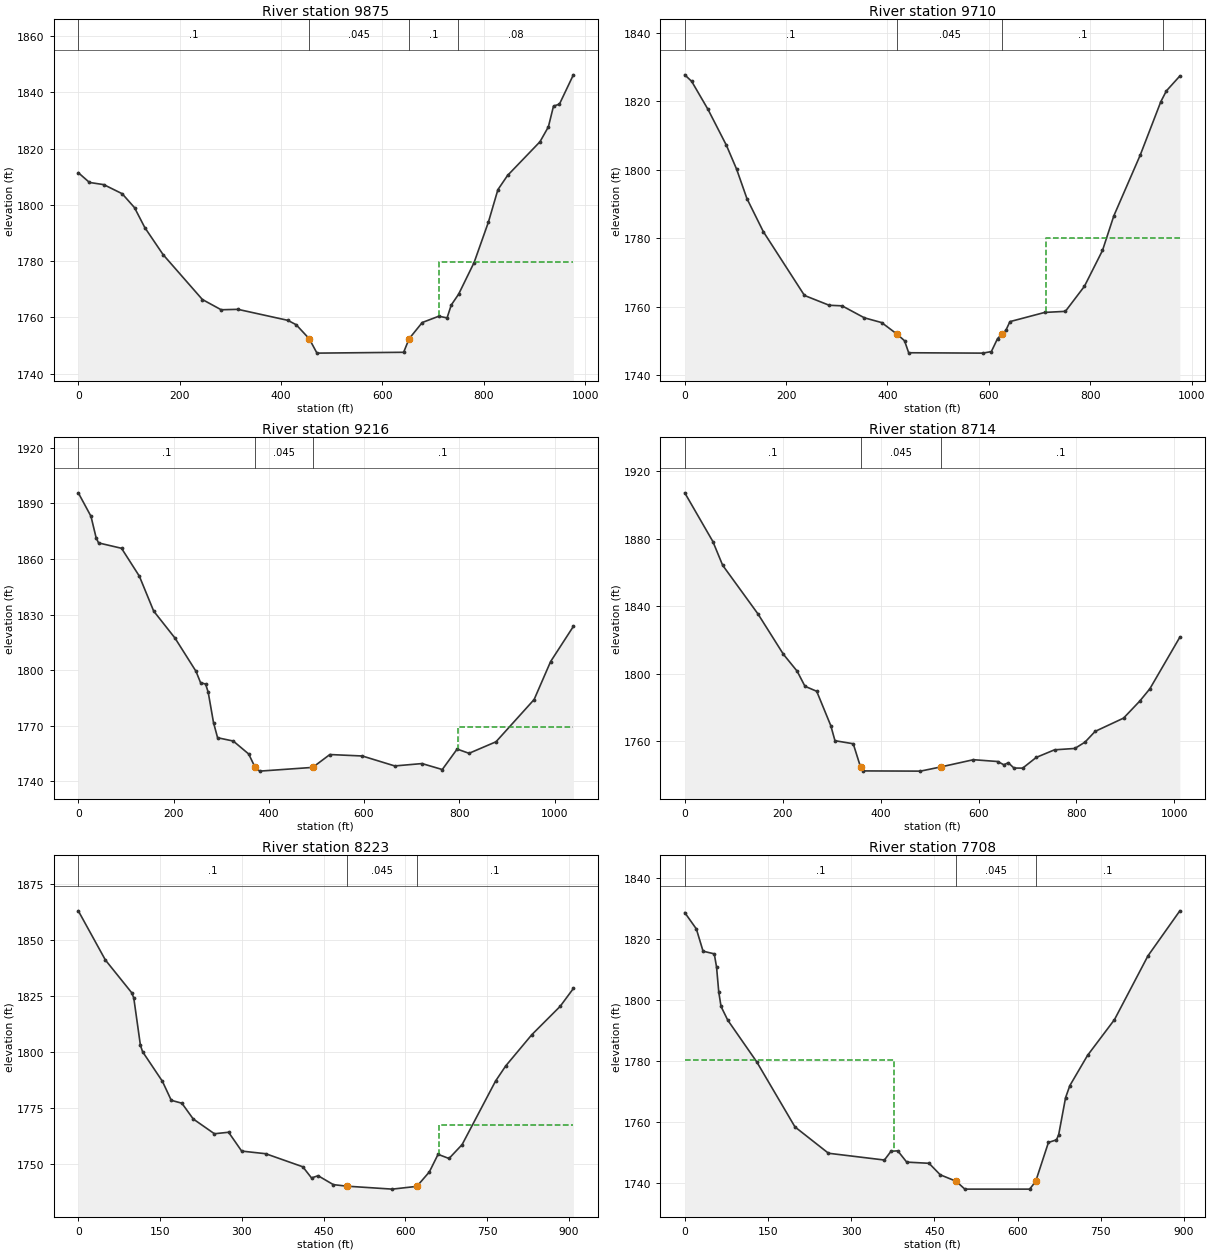
Type RM Length L Ch R = 1 ,9875    ,161.8,165.2,159.1
XS GIS Cut Line= 6
2255026.37651783715255.0282333222255236.11678856715284.508836514
2255360.53847761715253.4427151222255484.83278047715225.228670914
2255834.83943701715156.5999147312255977.98650135715103.552834569
#Sta/Elev= 30
       0 1811.45      22 1807.98    50.3  1807.2    86.6 1803.97   110.9 1799.02
   131.2 1791.93   167.4 1782.28   244.8 1766.33   281.9 1762.68   314.9 1762.83
   413.5 1758.91   429.9 1757.35  455.591752.382   470.9 1747.25   641.9 1747.55
  652.781752.383   678.6 1758.14   711.3 1760.38   727.6 1759.78   735.8 1764.35
   750.4 1768.23   780.9 1779.47   809.2 1793.89   827.9 1805.42   846.9 1810.46
   910.9 1822.46   927.5 1827.76   937.6 1835.14   949.3 1835.84   976.8 1846.27
#Mann= 4 ,-1,0
       0      .1       0  455.59    .045       0  652.78      .1       0
  749.56     .08       0
#XS Ineff= 2 , 0
                          712.64         1779.76
Permanent Ineff=
       F       F
Bank Sta=455.59,652.78
XS Rating Curve= 0 ,0
Exp/Cntr=0.3,0.1

Type RM Length L Ch R = 1 ,9710    ,527.1,493.8,429.8
XS GIS Cut Line= 6
 2255054.7437338715408.6164454852255264.48400453715438.097048677
2255388.90569358715407.0309272852255513.19999644715378.816883077
2255863.20665297715310.1881268942256006.35371732715257.141046732
#Sta/Elev= 30
       0 1827.71    13.6 1825.81    45.9  1817.6    82.2 1807.12   102.4 1800.12
   122.6 1791.59   154.9 1781.94   236.2 1763.28   284.9 1760.42   310.4 1760.25
   354.4 1756.75   388.5 1755.36  419.18 1751.94   433.6 1750.06   441.8 1746.55
     588 1746.44   604.9 1746.89   617.1 1750.67   625.3 1751.94   633.4 1753.06
   641.6 1755.64   710.3 1758.33     751 1758.64   788.5 1765.95   824.2 1776.43
   846.5 1786.51   898.7 1804.29   939.3 1819.88   950.2 1823.01   976.8 1827.37
#Mann= 4 ,-1,0
       0      .1       0  419.18    .045       0   625.3      .1       0
  944.18     .08       0
#XS Ineff= 2 , 0
                           712.9         1779.99
Permanent Ineff=
       F       F
Bank Sta=419.18,625.3
XS Rating Curve= 0 ,0
Exp/Cntr=0.3,0.1

Type RM Length L Ch R = 1 ,9216    ,551.1,501.9,411.1
XS GIS Cut Line= 6
 2255412.3287197716094.3323044772255638.32588056715893.389948455
2255703.10599781715807.6516649622255964.14840069715498.880892111
 2256008.6884029715444.8739841892256066.99389508715300.869953716
#Sta/Elev= 30
       0  1895.7    26.6 1883.05    37.5 1871.38    42.6 1868.66    90.8 1865.76
   128.2 1850.72   158.3 1831.87   203.2 1817.24   247.2 1799.34   256.7 1793.24
   267.4 1792.45   272.8 1788.03     284 1771.59   292.5  1763.5   325.4 1761.71
   357.8 1754.72  371.131747.574     381 1745.47   492.1 1747.48   528.3 1754.43
   596.4 1753.64   664.5 1748.27   721.8 1749.55   764.3 1746.33   795.5 1757.37
   820.5 1755.09   877.1 1761.31   957.2 1784.13   991.8 1804.61  1039.6  1823.6
#Mann= 3 ,-1,0
       0      .1       0  371.13    .045       0   492.1      .1       0
#XS Ineff= 2 , 0
                             798         1769.35
Permanent Ineff=
       F       F
Bank Sta=371.13,492.1
XS Rating Curve= 0 ,0
Exp/Cntr=0.3,0.1

Type RM Length L Ch R = 1 ,8714    ,477.1,491.6,512.8
XS GIS Cut Line= 4
 2256217.6338459716338.5377422492256207.84035749 716059.57893542
2256125.52504593715773.618543667     2256238.663      715354.108
#Sta/Elev= 30
       0 1907.18    57.4 1878.33    77.4 1864.26   149.5 1835.44   201.5 1811.51
   229.5 1801.52   245.5 1792.57   269.5 1789.59   298.3  1769.2   306.8 1760.31
   344.1  1758.5   359.1 1744.65   364.9 1742.41   481.4 1742.28   522.8 1744.75
   589.6 1749.05   639.3 1747.97   651.7 1746.04   660.8 1747.24   672.4 1744.11
   690.2 1744.06     718 1750.42   755.3 1754.91   796.7 1755.71   817.5 1759.46
   838.2 1765.83   896.2 1773.68   929.3 1783.77     950 1791.09  1011.2 1821.64
#Mann= 3 ,-1,0
       0      .1       0   359.1    .045       0   522.8      .1       0
Bank Sta=359.1,522.8
XS Rating Curve= 0 ,0
Exp/Cntr=0.3,0.1

Type RM Length L Ch R = 1 ,8223    ,510.9,514.5,520.8
XS GIS Cut Line= 4
2256560.24305723716273.8308866932256601.81375267 716001.20480447
2256622.84570264715557.2791222982256622.36719743715368.998900713
#Sta/Elev= 30
       0 1863.18    49.7 1841.23    97.8 1826.68   101.8  1824.3     114 1803.15
     118 1800.28   154.4 1787.05   170.6 1778.59   190.1 1777.29   210.9 1770.26
   249.8 1763.66   275.8 1764.33   299.8 1755.92   343.9 1754.75     412 1748.91
     428 1743.93     440 1744.93     468 1740.95   492.2 1740.27   576.1 1738.94
  621.231740.168   644.2 1746.62   660.2 1754.47   680.3 1752.62   704.3 1758.81
   765.7 1787.18   784.3 1793.93   832.3  1807.9   884.3 1820.55   908.5 1828.51
#Mann= 3 ,-1,0
       0      .1       0   492.2    .045       0  621.23      .1       0
#XS Ineff= 2 , 0
                          661.29         1767.39
Permanent Ineff=
       F       F
Bank Sta=492.2,621.23
XS Rating Curve= 0 ,0
Exp/Cntr=0.3,0.1

Type RM Length L Ch R = 1 ,7708    ,479.4,471.5,464.9
XS GIS Cut Line= 4
2257057.18328797 716321.851552292257083.06415186  716144.3536306
2257143.78685836715641.6566962332257164.74400263715435.958691019
#Sta/Elev= 30
       0 1828.54    20.9 1823.19      33  1815.9    53.2 1815.03    57.3 1810.72
    61.3 1802.52    65.4  1797.8    77.5 1793.31   129.8 1779.64   198.7 1758.34
   259.1 1749.72   359.9  1747.5   371.9 1750.39     384 1750.51   400.1 1746.82
   440.4 1746.43   460.6 1742.66  489.271740.548   504.9 1737.97   621.8 1737.97
   632.6  1740.5   655.6 1753.26   670.1 1754.11   674.1 1755.83   686.5 1767.92
   694.2 1771.88   726.1 1781.77   774.7  1793.5     835 1814.37   892.5 1829.12
#Mann= 3 ,-1,0
       0      .1       0  489.27    .045       0   632.6      .1       0
#XS Ineff= 2 , 0
          377.62 1780.35
Permanent Ineff=
       F       F
Bank Sta=489.27,632.6
XS Rating Curve= 0 ,0
Exp/Cntr=0.3,0.1

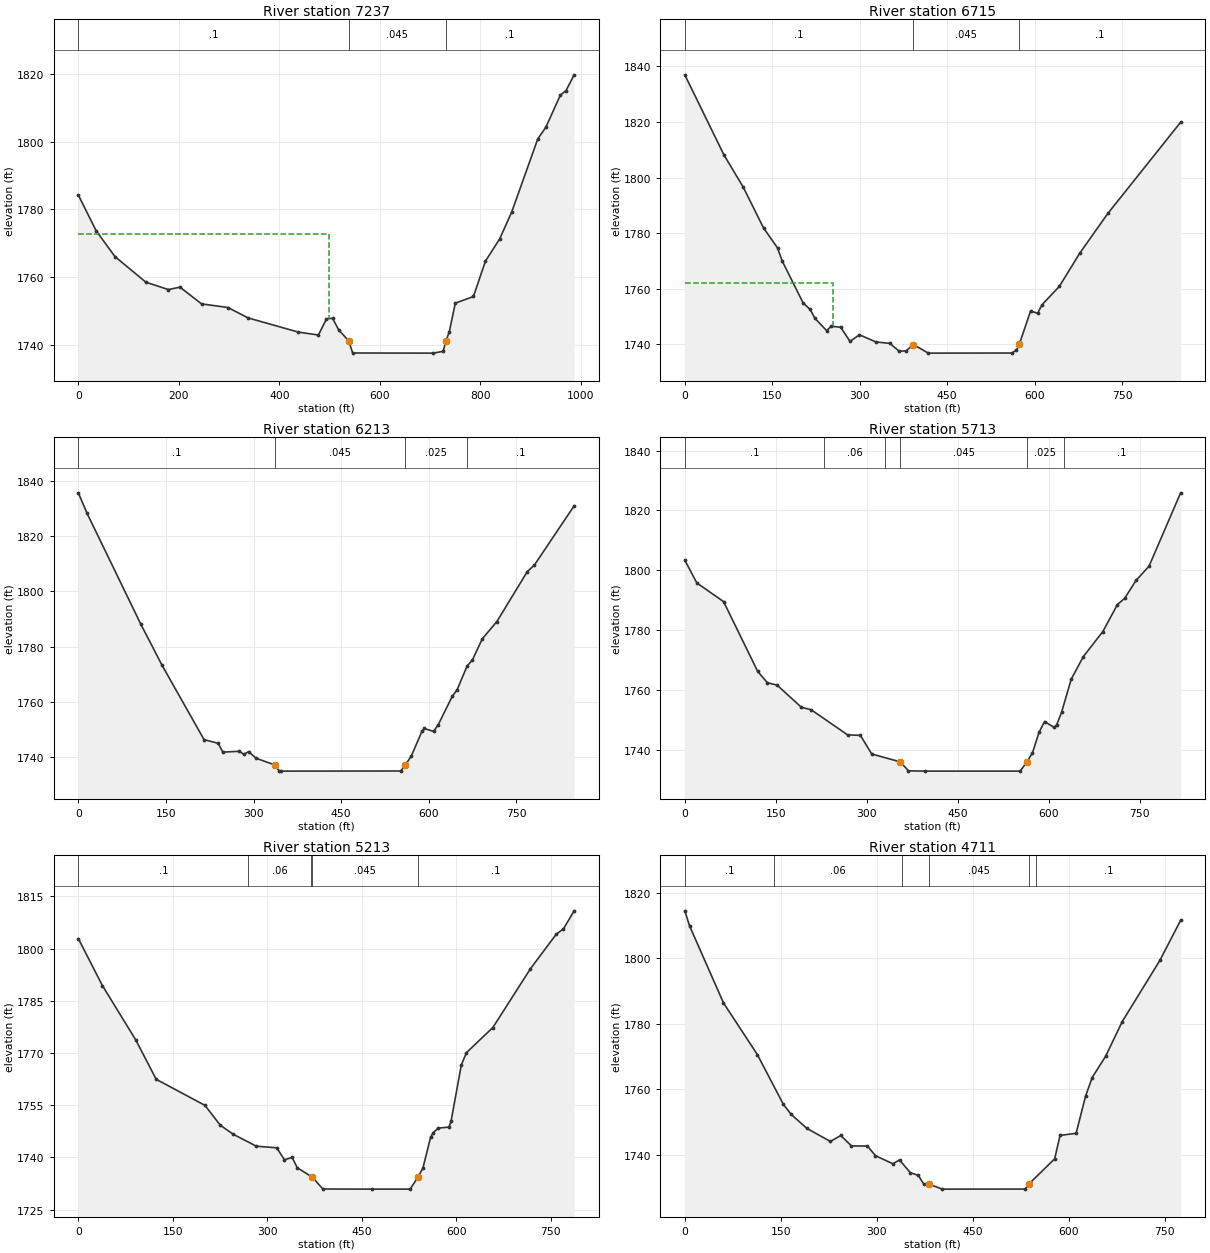
Type RM Length L Ch R = 1 ,7237    ,536.5,521.9,506
XS GIS Cut Line= 4
2257397.17062589716379.3204936372257570.59021828716260.593098024
2257602.15614661715702.2721757982257591.79772429715484.932548495
#Sta/Elev= 30
       0 1784.21    35.4 1773.68    72.8 1766.05   134.5 1758.46   179.2 1756.29
   202.4    1757   245.2 1752.06   297.7 1750.99   337.8 1747.92   437.9 1743.72
     478 1742.86     494 1747.64   506.1 1747.81   518.1 1744.41   538.1 1741.14
   546.1 1737.55   706.4 1737.51   726.4 1738.05  731.441741.013   738.4 1743.79
   750.4 1752.27   786.5 1754.24   810.5 1764.72   838.6 1771.22   862.6 1779.16
   914.6 1800.81   930.7 1804.26   959.6 1813.75   970.7 1815.05     987 1819.73
#Mann= 3 ,-1,0
       0      .1       0   538.1    .045       0  731.44      .1       0
#XS Ineff= 2 , 0
          498.19 1772.66
Permanent Ineff=
       F       F
Bank Sta=538.1,731.44
XS Rating Curve= 0 ,0
Exp/Cntr=0.3,0.1

Type RM Length L Ch R = 1 ,6715    ,503.4,501.9,505
XS GIS Cut Line= 4
 2258140.0212903      716256.1752258137.81901188716041.494508493
2258100.16714661715661.5357476432258078.02728446715408.781129097
#Sta/Elev= 30
       0 1836.99      67 1808.19   100.2 1796.54     135 1781.83     159 1774.64
     167 1769.93     203 1754.78     215 1752.48     223 1749.31   243.1 1744.87
   251.2 1746.41   267.3 1746.07   283.3 1740.95   299.4 1743.36   327.6 1740.77
   351.7 1740.24   367.8 1737.38   379.8 1737.59     392 1739.83   417.6 1736.74
   560.7 1736.78   568.7 1737.79  573.561739.884   592.9 1751.91   604.9  1751.1
   612.9 1754.25   642.3  1760.8   677.2 1772.73   725.4 1787.05   850.2 1819.91
#Mann= 3 ,-1,0
       0      .1       0     392    .045       0  573.56      .1       0
#XS Ineff= 2 , 0
          253.78 1762.07
Permanent Ineff=
       F       F
Bank Sta=392,573.56
XS Rating Curve= 0 ,0
Exp/Cntr=0.3,0.1

Type RM Length L Ch R = 1 ,6213    ,500.6,500,501.1
XS GIS Cut Line= 3
     2258646.064      716220.008     2258614.699       715766.09
2258585.30125351715373.187858654
#Sta/Elev= 30
       0 1835.63    14.9 1828.23   107.1 1788.04   143.1 1773.32   215.3 1746.31
   239.4    1745   247.4 1741.81   275.5  1742.1   283.5 1740.99   291.5 1741.98
   304.5 1739.57  336.66 1737.14   343.6 1735.05   347.7 1734.92   552.2 1734.97
  560.011737.141   570.2  1740.4   588.3 1749.29   592.3 1750.36   608.3 1749.28
   616.4 1751.78   640.4 1762.04   648.5 1764.33   665.7 1772.96   674.7 1775.12
   691.7  1782.8   716.6 1789.03   768.8 1807.14   780.8 1809.46     849 1830.93
#Mann= 4 ,-1,0
       0      .1       0  336.66    .045       0  560.01    .025       0
   665.7      .1       0
Bank Sta=336.66,560.01
XS Rating Curve= 0 ,0
Exp/Cntr=0.3,0.1

Type RM Length L Ch R = 1 ,5713    ,510.8,500,489.1
XS GIS Cut Line= 3
     2259145.588      716185.058     2259113.479      715731.192
2259090.11779336715369.178830231
#Sta/Elev= 30
       0 1803.36    19.9 1795.75      64 1789.52   120.2 1766.19   136.2 1762.41
   152.3 1761.59   192.4 1754.17   208.4 1753.37   268.5 1744.96   289.6 1744.81
   308.3 1738.57  355.741735.912   368.8 1732.94   396.9 1732.84   553.2 1732.84
  564.121735.911   573.3 1738.86   584.3 1745.82   593.3 1749.41   609.3 1747.46
   613.3  1748.3   621.4 1752.49   637.4 1763.59   657.4 1771.16   689.5 1779.51
   713.5 1788.51   725.5 1790.62   744.3 1796.61   765.7 1801.37   817.8 1825.89
#Mann= 6 ,-1,0
       0      .1       0     230     .06       0     330      .1       0
  355.74    .045       0  564.12    .025       0     625      .1       0
Bank Sta=355.74,564.12
XS Rating Curve= 0 ,0
Exp/Cntr=0.3,0.1

Type RM Length L Ch R = 1 ,5213    ,511.2,502.4,493.2
XS GIS Cut Line= 3
     2259694.793       716118.69     2259609.396      715671.775
2259548.53405137715344.958514588
#Sta/Elev= 30
       0 1802.86    38.2 1789.36    91.1 1773.77   123.7 1762.43   201.1 1754.94
   225.5 1749.23   245.9 1746.66   282.5 1743.22   315.1 1742.75   327.3  1739.3
   339.5 1739.99   347.7 1737.03  371.791734.278   388.4 1730.91   465.8 1730.88
   526.9 1730.88  539.231734.279   547.2 1736.92   559.4 1745.77   563.4 1747.07
   571.7 1748.42   588.6  1748.7   591.9 1750.39   608.2 1766.54   616.3 1770.08
   658.3 1777.31     718  1794.2   758.7 1804.05   770.4 1805.67   787.4 1810.83
#Mann= 5 ,-1,0
       0      .1       0     270     .06       0     370      .1       0
  371.79    .045       0  539.23      .1       0
Bank Sta=371.79,539.23
XS Rating Curve= 0 ,0
Exp/Cntr=0.3,0.1

Type RM Length L Ch R = 1 ,4711    ,464.1,497.1,525.9
XS GIS Cut Line= 4
2260204.81671834715988.3922816612260156.11641304715743.772236741
2260053.60342053 715407.704064442260002.67156096715240.877966901
#Sta/Elev= 30
       0 1814.58     7.4    1810    60.4 1786.44   113.4 1770.61   154.2 1755.35
   166.4 1752.28   190.9 1748.02   227.6 1744.03   243.9 1745.85   260.5 1742.66
   285.6 1742.62   298.1 1739.67   325.2  1737.2   335.8 1738.37   352.5 1734.48
     365 1733.66   373.4 1731.04   381.8 1730.95   402.7 1729.44   532.3 1729.46
  538.07 1731.03   578.3 1738.72   586.7 1745.88   611.8 1746.51   626.5 1757.84
   636.9 1763.58   657.8 1770.04     684 1780.72   742.7  1799.4   775.2 1811.68
#Mann= 6 ,-1,0
       0      .1       0     140     .06       0  339.42      .1       0
   381.8    .045       0  538.07    .025       0  549.42      .1       0
Bank Sta=381.8,538.07
XS Rating Curve= 0 ,0
Exp/Cntr=0.3,0.1

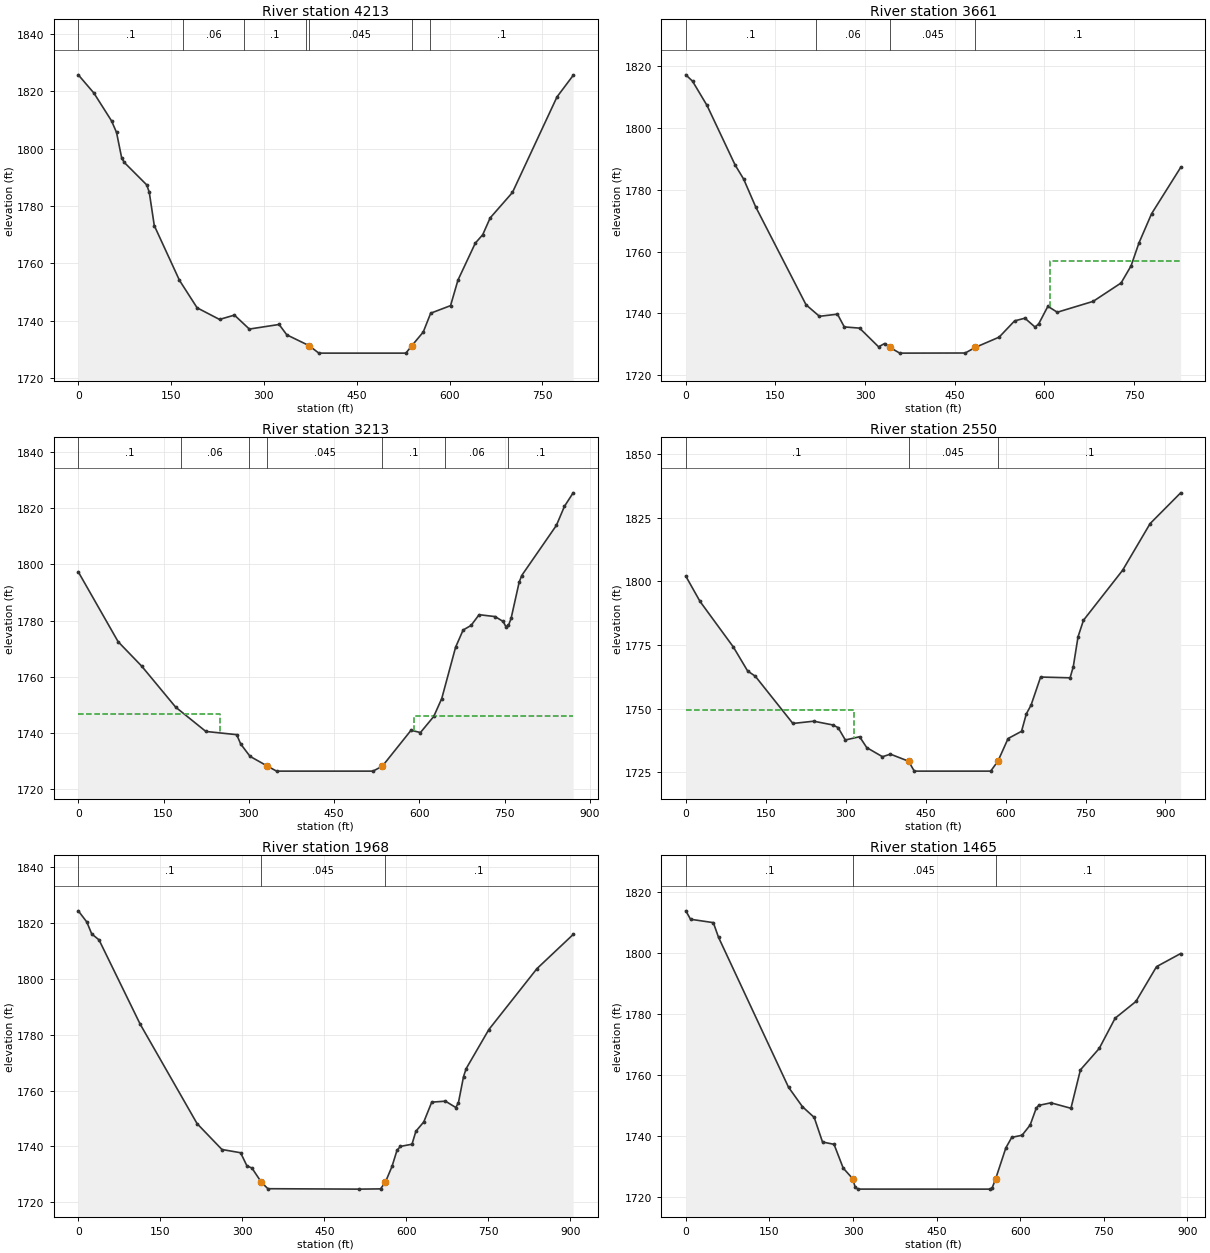
Type RM Length L Ch R = 1 ,4213    ,484.1,552.2,613.9
XS GIS Cut Line= 4
      2260524.33         715922.2260560.12022556 715727.06324276
2260592.84578729715339.7294452562260587.51171846715127.108449782
#Sta/Elev= 30
       0 1825.69    25.2 1819.35    53.7 1809.67    61.8 1805.63      70 1796.87
      74 1795.25   110.6 1787.36   114.7 1784.81   122.8 1773.19   163.5 1754.13
     192 1744.56   228.2 1740.51   252.3 1742.02   276.4 1737.16   324.5 1738.76
   336.9 1735.15   372.7 1731.41   388.7 1728.78   529.3 1728.78  538.941731.365
   557.4 1736.13   569.4 1742.68   601.5 1745.32   613.5 1754.22   641.5 1767.08
   653.5 1770.02   665.5 1775.86   701.5 1784.72   773.5    1818   799.6 1825.49
#Mann= 7 ,-1,0
       0      .1       0     170     .06       0   268.2      .1       0
   368.2     .05       0   372.7    .045       0  538.94    .025       0
   568.2      .1       0
Bank Sta=372.7,538.94
XS Rating Curve= 0 ,0
Exp/Cntr=0.3,0.1

Type RM Length L Ch R = 1 ,3661    ,439.6,448.3,460
XS GIS Cut Line= 4
2260703.92073717715996.5778851972260860.91753846715877.417521217
2261235.41516459715587.5764465842261288.49312385715439.379114803
#Sta/Elev= 30
       0 1817.19    11.2 1815.15    35.5 1807.28    82.5 1788.03    96.8 1783.46
   116.8 1774.53   201.2  1742.8   223.6 1739.07   253.8 1739.76   265.2 1735.64
   290.8 1735.25   322.6  1729.2   332.7 1730.27   341.3 1729.04     358 1727.16
   467.6  1727.2   484.5 1729.02   524.3 1732.33   550.2 1737.59   567.4 1738.46
   584.5 1735.58   590.7 1736.69   605.9 1742.31   621.6 1740.39   681.7 1743.91
   728.4 1749.86   745.1  1755.4   758.2 1762.76   779.4 1772.25   828.1 1787.24
#Mann= 4 ,-1,0
       0      .1       0   217.1     .06       0   341.3    .045       0
   484.5      .1       0
#XS Ineff= 2 , 0
                          608.91         1756.88
Permanent Ineff=
       F       F
Bank Sta=341.3,484.5
XS Rating Curve= 0 ,0
Exp/Cntr=0.3,0.1

Type RM Length L Ch R = 1 ,3213    ,656.6,662.6,671.7
XS GIS Cut Line= 3
2260921.54570678716334.856433992     2261277.424      716119.844
     2261665.189      715881.803
#Sta/Elev= 30
       0 1797.31    70.1 1772.47   111.5  1763.8   171.3 1749.21   224.5 1740.55
   278.8 1739.41   285.7 1736.12   302.2  1731.7   332.3 1728.28   348.9 1726.44
   518.6 1726.44  535.01 1728.19   585.5 1740.96   602.1 1740.17   625.5 1745.88
   639.6 1752.27     664 1770.54   677.2 1776.63   691.2 1778.26   705.3 1782.08
   733.5  1781.4   747.6 1779.67   752.3 1777.87     757 1778.26   761.6 1780.75
   775.7 1793.55   780.3 1796.01   841.4 1813.87   855.5 1820.62   870.8 1825.42
#Mann= 7 ,-1,0
       0      .1       0     180     .06       0     300    .025       0
   332.3    .045       0  535.01      .1       0  645.79     .06       0
  755.79      .1       0
#XS Ineff= 2 , 0
          248.58 1746.62  590.18         1746.14
Permanent Ineff=
       F       F
Bank Sta=332.3,535.01
XS Rating Curve= 0 ,0
Exp/Cntr=0.3,0.1

Type RM Length L Ch R = 1 ,2550    ,586.4,582.2,578.6
XS GIS Cut Line= 2
2261176.30127623716908.1543906172262007.42238484716494.234353658
#Sta/Elev= 30
       0 1802.08    26.7 1792.13    89.2 1774.21     116 1764.78   130.4 1762.71
   200.9 1744.13     240 1745.02   275.9 1743.54   285.8 1742.49   299.3 1737.63
   326.1 1738.91   339.5 1734.63     369 1731.05   383.9 1732.06  417.931729.285
   428.7 1725.38     572 1725.38  585.611729.286   604.7 1738.21   629.9 1741.04
   638.9  1747.9   647.8 1751.36   665.7 1762.39     721 1762.09     727 1766.45
   735.9 1778.21   746.1 1784.72   819.5 1804.38   871.2 1822.77   928.5 1834.86
#Mann= 3 ,-1,0
       0      .1       0  417.93    .045       0  585.61      .1       0
#XS Ineff= 2 , 0
          314.94 1749.36
Permanent Ineff=
       F       F
Bank Sta=417.93,585.61
XS Rating Curve= 0 ,0
Exp/Cntr(USF)=0,0
Exp/Cntr=0.3,0.1

Type RM Length L Ch R = 1 ,1968    ,525.3,502.9,476.9
XS GIS Cut Line= 4
2261510.29562702717403.3291981352261715.32241282717299.615376756
2262054.30614526717111.4425800062262297.67776885716957.819907394
#Sta/Elev= 30
       0 1824.42    15.6 1820.42    24.5 1816.17      38 1813.99   113.1 1783.85
   217.3 1748.17   262.8 1738.89   296.9 1737.73   308.5 1733.04   317.7 1732.24
  334.971727.152   346.9 1724.84   513.6 1724.69   552.9 1724.78  561.72 1727.15
   573.9 1732.81     583 1738.56   589.2    1740   610.5 1740.78   617.6 1745.43
   632.1 1748.79   646.6 1755.86   671.7 1756.21   690.6 1753.94   695.4 1755.64
   704.8 1765.03   709.6 1767.88     751 1781.85     839 1803.69   905.3 1815.94
#Mann= 3 ,-1,0
       0      .1       0  334.97    .045       0  561.72      .1       0
Bank Sta=334.97,561.72
XS Rating Curve= 0 ,0
Exp/Cntr(USF)=0,0
Exp/Cntr=0.3,0.1

Type RM Length L Ch R = 1 ,1465    ,492.6,464.8,450.9
XS GIS Cut Line= 4
2261844.07832295717782.8355510382262067.82141477717713.691336419
2262342.03849308717474.5485355672262556.13224422717279.007637927
#Sta/Elev= 30
       0 1813.98     8.5 1811.21    49.4  1810.1    58.7 1805.29   184.3 1756.06
   209.3 1749.66   230.4 1746.14   245.3 1738.07     266  1737.3   282.4 1729.51
  299.61 1725.99   303.6 1723.39   308.5  1722.6   545.3 1722.59   549.5 1722.88
  556.011725.992   574.3 1736.14   584.9  1739.6   603.3 1740.27   617.9 1743.63
   628.8 1749.18   633.4 1750.09   655.1 1750.93   691.1 1749.14   708.1 1761.75
   741.8 1768.78   770.4 1778.72   807.7 1784.21   844.7 1795.65     888 1799.96
#Mann= 3 ,-1,0
       0      .1       0  299.61    .045       0  556.01      .1       0
Bank Sta=299.61,556.01
XS Rating Curve= 0 ,0
Exp/Cntr(USF)=0,0
Exp/Cntr=0.3,0.1