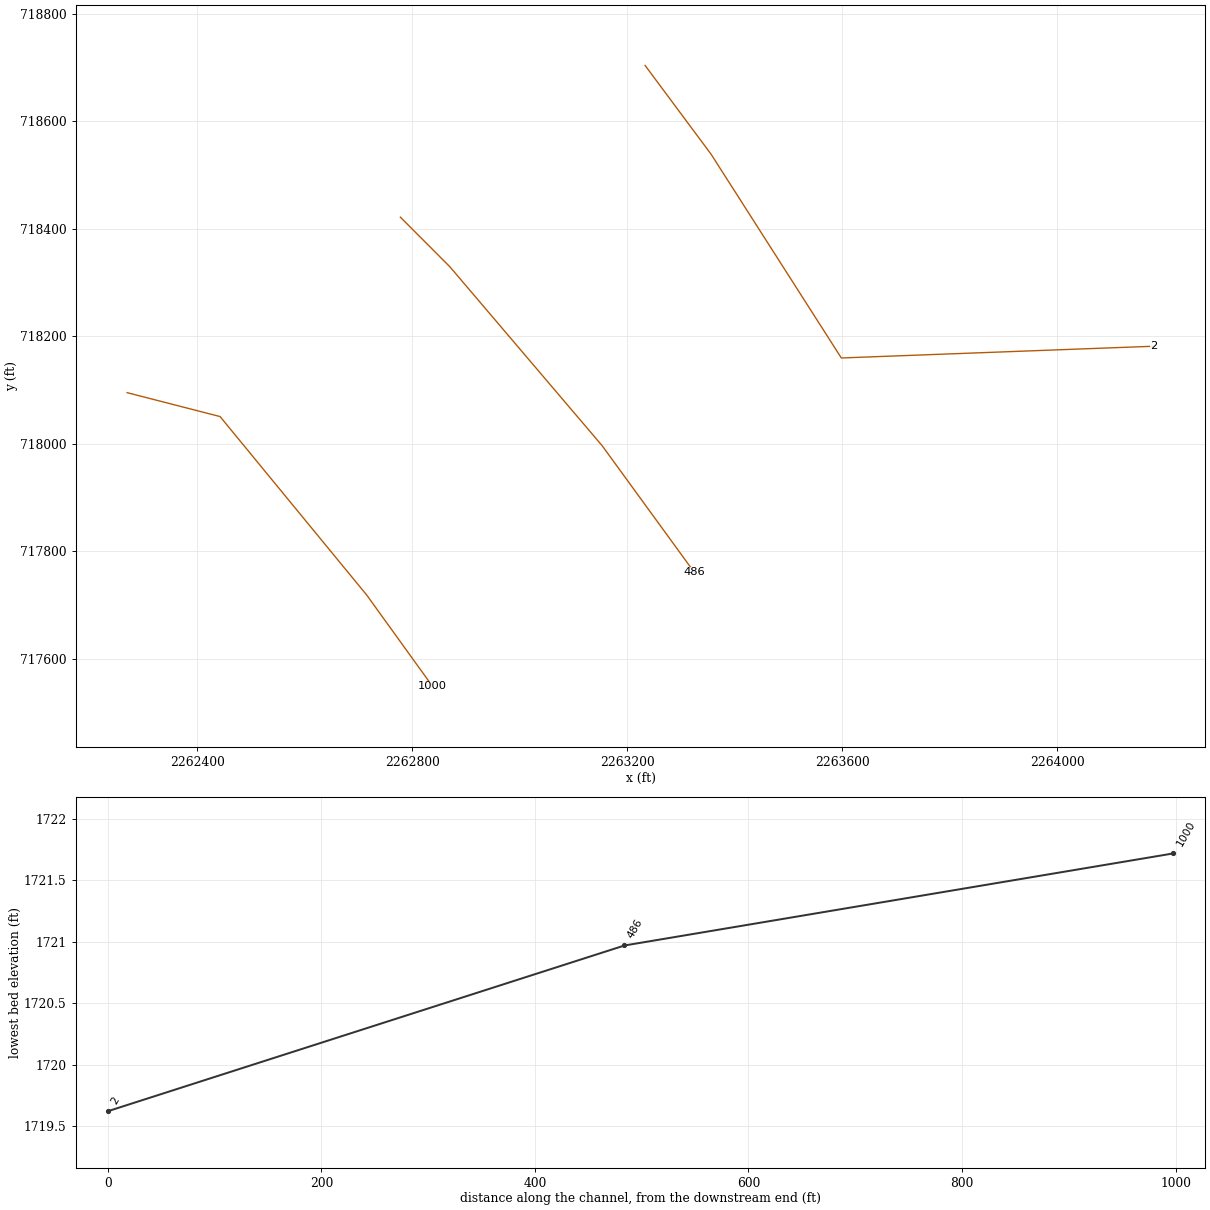
HEC-RAS study TYGVRV1.prj: TYGVRV1

--- TYGVRV1.g01 (geometry) --- (continued)

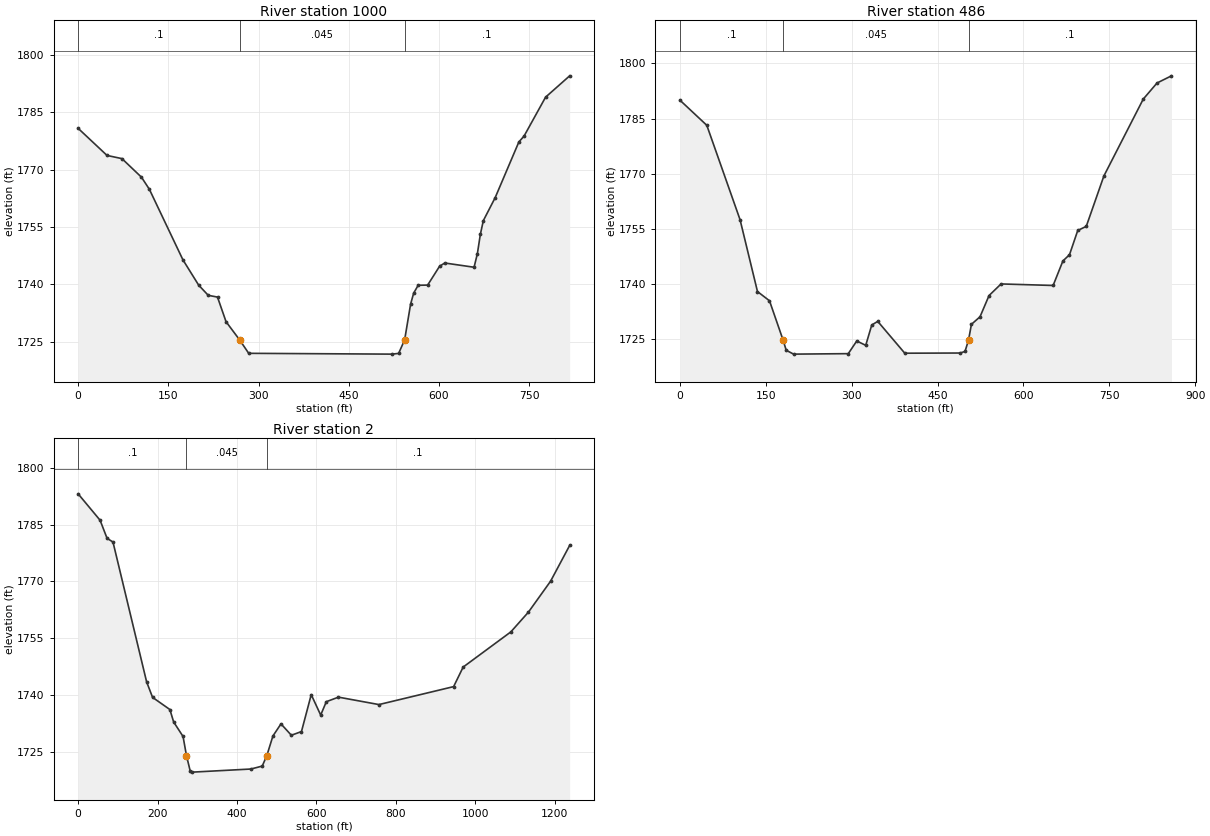
Type RM Length L Ch R = 1 ,1000    ,508.4,514.1,518
XS GIS Cut Line= 4
2262269.60846036 718094.898507292262442.52077592718050.417426878
2262715.51129967717718.1164009262262837.67248803717548.652787193
#Sta/Elev= 30
       0 1780.82    48.1 1773.72    72.9 1772.89   105.4 1768.02   118.5 1764.86
   174.3  1746.4   200.5 1739.77   216.4 1737.11   231.8 1736.65     246 1730.21
  268.611725.443   283.7 1721.93   521.4 1721.72     533  1721.9  543.021725.442
   552.9 1734.78     558 1737.67   565.5 1739.74   581.3 1739.79   601.2 1744.74
   609.8 1745.57   658.5 1744.46     664 1748.01   668.9 1753.04   673.9 1756.66
   693.6 1762.68     733 1777.26   741.6 1778.78   777.4 1788.97   817.5 1794.56
#Mann= 3 ,-1,0
       0      .1       0  268.61    .045       0  543.02      .1       0
Bank Sta=268.61,543.02
XS Rating Curve= 0 ,0
Exp/Cntr(USF)=0,0
Exp/Cntr=0.3,0.1

Type RM Length L Ch R = 1 ,486     ,527.3,483.9,471.7
XS GIS Cut Line= 4
2262777.95945582718421.375949792 2262870.0468175718329.121682701
2263153.47532221717996.0931896622263324.61870739717760.831539106
#Sta/Elev= 30
       0 1790.01      47 1783.17   105.1  1757.5   135.5 1737.98   156.5 1735.47
  180.16 1724.82   185.7 1722.02   198.6 1720.97   294.1  1721.1   308.9 1724.54
   324.6 1723.36   335.1 1728.89   345.6 1729.87   392.8 1721.22   489.4 1721.27
     498  1721.7   504.21724.822   509.2 1729.07   524.2 1731.12     540  1736.9
     561 1740.05   651.9 1739.63     669  1746.3   680.5 1747.99   694.9 1754.58
   709.8  1755.7   740.6 1769.41   809.3 1790.29   833.4 1794.67   858.6 1796.62
#Mann= 3 ,-1,0
       0      .1       0  180.16    .045       0   504.2      .1       0
Bank Sta=180.16,504.2
XS Rating Curve= 0 ,0
Exp/Cntr(USF)=0,0
Exp/Cntr=0.3,0.1

Type RM Length L Ch R = 1 ,2       ,,,
XS GIS Cut Line= 4
2263233.31233253718703.6648104682263356.32296312  718538.1254603
2263598.35550729 718159.426961242264180.23549098718181.313135666
#Sta/Elev= 30
       0 1793.11    55.3 1786.14    72.9 1781.36    87.8 1780.38   172.5 1743.46
   187.5 1739.36   231.1 1736.15   240.6 1732.86   264.3 1729.03   272.91723.971
   282.1    1720   287.9 1719.62   435.2 1720.44   463.7 1721.22  475.211723.967
   490.6 1729.16   510.9 1732.36     537 1729.36   562.5 1730.33   587.1 1740.08
   610.9 1734.69   625.1 1738.22   655.7 1739.42   757.6 1737.46   945.7  1742.2
   969.7 1747.36  1089.8 1756.65  1134.1 1761.87  1189.9 1770.04    1238 1779.49
#Mann= 3 ,-1,0
       0      .1       0   272.9    .045       0  475.21      .1       0
Bank Sta=272.9,475.21
XS Rating Curve= 0 ,0
Exp/Cntr(USF)=0,0
Exp/Cntr=0.3,0.1
LCMann Table=0

Chan Stop Cuts=-1
Use User Specified Reach Order=0
Composite Channel Slope=5